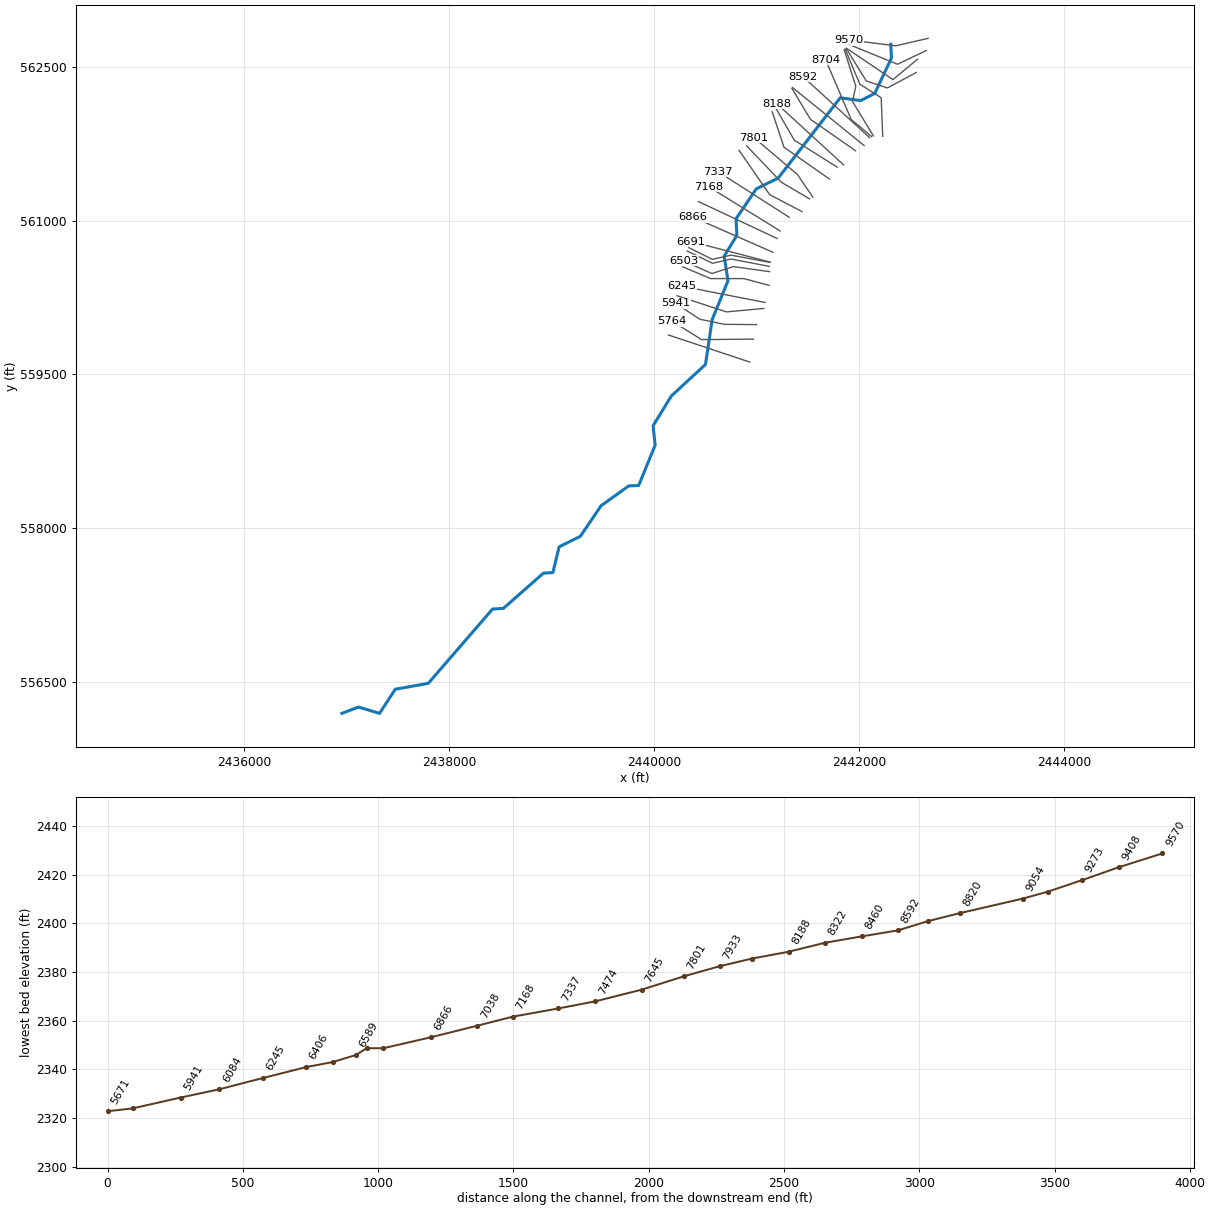
--- STAUFLERN.prj (project) ---

Proj Title=STAUFLERN
Current Plan=p01
Default Exp/Contr=0,0
English Units
Geom File=g01
Flow File=f01
Plan File=p01
BEGIN DESCRIPTION:
Stream Name: Stauffles Run
Flood Zone: Approximate
Pendlteon County, West Virginia
HEC-RAS Version: 5.0.7
Hydrology Method:
Regression
END DESCRIPTION:
DSS Export Rating Curves= 0
DSS Export Rating Curve Sorted= 0
DSS Export Volume Flow Curves= 0
DXF OffsetX= 0
DXF OffsetY= 0
DXF ScaleX= 0
DXF ScaleY= 0

--- STAUFLERN.p01 (plan) ---

Plan Title=Floodplain
Program Version=5.07
Short Identifier=Floodplain
Geom File=g01
Flow File=f01
Subcritical Flow
K Sum by GR= 0
Std Step Tol= 0.01
Critical Tol= 0.01
Num of Std Step Trials= 20
Max Error Tol= 0.3
Flow Tol Ratio= 0.001
Split Flow NTrial= 30
Split Flow Tol= 0.02
Split Flow Ratio= 0.02
Log Output Level= 0
Friction Slope Method= 1
Unsteady Friction Slope Method= 2
Unsteady Bridges Friction Slope Method= 1
Parabolic Critical Depth
Global Vel Dist= 0 , 0 , 0
Global Log Level= 0
CheckData=False
Encroach Param=-1 ,0,0, 0
Mapping Interval=1HOUR
Computation Time Step Use Courant=        0
Computation Time Step Use Time Series=    0
Computation Time Step Count To Double=0
Computation Time Step Max Doubling=0
Computation Time Step Max Halving=0
Computation Time Step Residence Courant=0
Run HTab= 0
Run UNet= 0
Run Sediment= 0
Run PostProcess= 0
Run WQNet= 0
Run RASMapper= 0
UNET Theta= 0
UNET Theta Warmup= 0
UNET ZTol= 0
UNET ZSATol= 0
UNET MxIter= 0
UNET Max Iter WO Improvement= 0
UNET MaxInSteps= 0
UNET DtIC= 0
UNET DtMin= 0
UNET MaxCRTS= 0
UNET WFStab= 0
UNET SFStab= 0
UNET WFX= 1
UNET SFX= 1
UNET 1D Methodology=Finite Difference
UNET DSS MLevel= 1
UNET Pardiso=0
UNET DZMax Abort= 0
UNET Use Existing IB Tables= 0
UNET Froude Reduction=False
UNET Froude Limit= 0
UNET Froude Power= 0
UNET D1 Cores= 0
UNET D2 Coriolis=0
UNET D2 Cores= 0
UNET D2 Theta= 1
UNET D2 Theta Warmup= 1
UNET D2 Z Tol= 0.01
UNET D2 Volume Tol= 0.01
UNET D2 Max Iterations= 20
UNET D2 Equation= 0
UNET D2 RampUpFraction=0.1
UNET D2 TimeSlices= 1
UNET D2 BCVolumeCheck=0
UNET D1D2 MaxIter= 0
UNET D1D2 ZTol=0.01
UNET D1D2 QTol=0.1
UNET D1D2 MinQTol=1
Write IC File= 0
Write IC File at Fixed DateTime=0
Write IC File at Sim End=0
Echo Input=False
Echo Parameters=False
Echo Output=False
Write Detailed= 0
HDF Write Warmup=0
HDF Write Time Slices=0
HDF Flush=0
HDF Face Node Velocities=0
HDF Compression= 1
HDF Chunk Size= 1
HDF Spatial Parts= 1
HDF Use Max Rows=0
HDF Fixed Rows= 1
Calibration Method= 0
Calibration Iterations= 20
Calibration Max Change=0.05
Calibration Tolerance=0.2
Calibration Maximum=1.5
Calibration Minimum=0.5
Calibration Optimization Method= 1
WQ AD Non Conservative
WQ ULTIMATE=-1
WQ Max Comp Step=1HOUR
WQ Output Interval=15MIN
WQ Output Selected Increments= 0
WQ Output face flow=0
WQ Output face velocity=0
WQ Output face area=0
WQ Output face dispersion=0
WQ Output cell volume=0
WQ Output cell surface area=0
WQ Output cell continuity=0
WQ Output cumulative cell continuity=0
WQ Output face conc=0
WQ Output face dconc_dx=0
WQ Output face courant=0
WQ Output face peclet=0
WQ Output face adv mass=0
WQ Output face disp mass=0
WQ Output cell mass=0
WQ Output cell source sink temp=0
WQ Output nsm pathways=0
WQ Output nsm derived pathways=0
WQ Output MaxMinRange=-1
WQ Daily Max Min Mean=-1
WQ Daily Range=0
WQ Daily Time=0
WQ Create Restart=0
WQ Fixed Restart=0
WQ System Summary=0
WQ Write To DSS=0
WQ Use Fixed Temperature=0
Sorting and Armoring Iterations= 10
XS Update Threshold= 0.02
Bed Roughness Predictor= 0
Hydraulics Update Threshold= 0.02
Energy Slope Method= 1
Volume Change Method= 1
Sediment Retention Method= 0
XS Weighting Method= 0
Number of US Weighted Cross Sections= 1
Number of DS Weighted Cross Sections= 1
Upstream XS Weight=0
Main XS Weight=1
Downstream XS Weight=0
Number of DS XS's Weighted with US Boundary= 1
Upstream Boundary Weight= 1
Weight of XSs Associated with US Boundary= 0
Number of US XS's Weighted with DS Boundary= 1
Downstream Boundary Weight= 0.5
Weight of XSs Associated with DS Boundary= 0.5
Percentile Method= 0
Sediment Output Level= 3
Mass or Volume Output= 0
Output Increment Type= 1
Profile and TS Output Increment= 1
XS Output Flag= 0
XS Output Increment= 10
Write Gradation File= 0
Read Gradation Hotstart= 0
Write HDF5 File= 1
Write Binary Output= 1
Write DSS Sediment File= 0
SV Curve= 0
Specific Gage Flag= 0

--- STAUFLERN.f01 (steady flow) ---

Flow Title=Flows
Program Version=5.07
Number of Profiles= 6
Profile Names=P100yr,P10yr,P25yr,P50yr,P500yr,P101yr
River Rch & RM=STAUFLERN,Main            ,9570
     433     203     287     358     633     527
River Rch & RM=STAUFLERN,Main            ,8704
     611     286     404     504     896     743
River Rch & RM=STAUFLERN,Main            ,7474
     686     320     453     566    1007     834
River Rch & RM=STAUFLERN,Main            ,4261
     878     408     579     724    1293    1069
River Rch & RM=STAUFLERN,Main            ,1178
     991     460     652     817    1461    1206
Boundary for River Rch & Prof#=STAUFLERN,Main            , 1
Up Type= 0
Dn Type= 3
Dn Slope=0.03783
Boundary for River Rch & Prof#=STAUFLERN,Main            , 2
Up Type= 0
Dn Type= 3
Dn Slope=0.03783
Boundary for River Rch & Prof#=STAUFLERN,Main            , 3
Up Type= 0
Dn Type= 3
Dn Slope=0.03783
Boundary for River Rch & Prof#=STAUFLERN,Main            , 4
Up Type= 0
Dn Type= 3
Dn Slope=0.03783
Boundary for River Rch & Prof#=STAUFLERN,Main            , 5
Up Type= 0
Dn Type= 3
Dn Slope=0.03783
Boundary for River Rch & Prof#=STAUFLERN,Main            , 6
Up Type= 0
Dn Type= 3
Dn Slope=0.03783
DSS Import GetInterval= 0
DSS Import GetPeak= 0
DSS Import FillOption= 0

--- STAUFLERN.g01 (geometry) ---

Geom Title=Geometry
Program Version=5.07

River Reach=STAUFLERN       ,Main
Reach XY= 30
     2442307.628      562722.056     2442314.387      562587.171
     2442151.257      562242.452     2442014.928      562171.709
     2441814.078      562199.052     2441209.415      561415.669
     2440995.851      561310.529     2440797.947      561018.381
      2440806.17       560856.37     2440682.129      560652.991
      2440719.56      560412.708     2440565.304      560035.251
     2440500.234      559596.295     2440166.892      559288.253
     2439989.008      558997.992     2440008.871      558808.542
      2439848.43       558415.02      2439750.25      558410.017
     2439481.796      558217.505     2439279.336       557918.91
     2439072.446      557815.975      2439011.12      557564.567
     2438919.033      557559.187      2438528.94       557215.39
     2438422.779       557208.69     2437795.627      556483.451
      2437474.01      556425.9992437320.15437278556190.374633146
     2437114.771      556252.147     2436953.253        556190.3

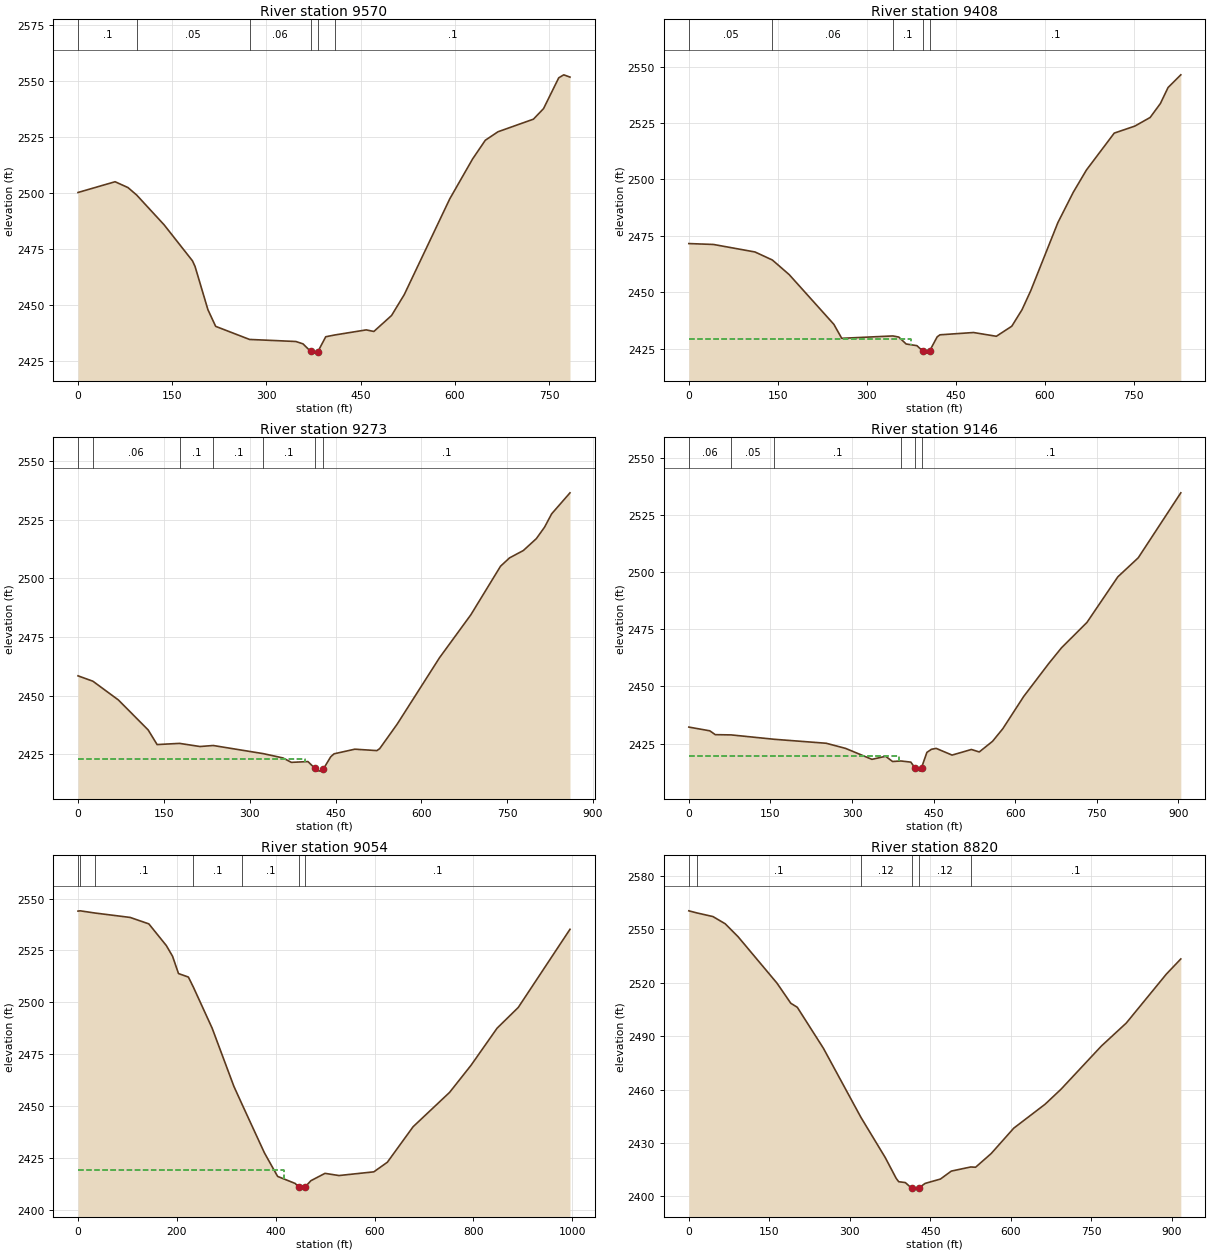
Type RM Length L Ch R = 1 ,9570    ,164.4,162.2,158.3
XS GIS Cut Line= 3
2442671.85601022562779.449845095 2442356.0447605562706.439879943
       2441900.6      562763.366
#Sta/Elev= 30
       0 2500.38      59 2505.18    79.5 2502.58   93.382499.236     137 2485.96
   182.2 2469.87   186.3 2467.35   206.8 2448.04   219.1 2440.61  273.012434.772
   346.8 2433.85   358.1  2432.8   370.2 2429.47   377.2 2428.66   381.8 2429.32
   394.3 2435.97  408.532436.755   458.8 2439.04   470.9 2438.33   499.1 2445.46
   519.3 2454.79   591.8 2497.58   628.1 2515.36   648.3  2523.7   668.4 2527.48
   724.9 2533.11     741 2537.83   765.2 2551.58   773.2 2552.91   783.1 2551.89
#Mann= 6 ,-1 , 0
       0      .1       0   93.38     .05       0  273.01     .06       0
   370.2    .045       0   381.8     .06       0  408.53      .1       0
Bank Sta=370.2,381.8
XS Rating Curve= 0 ,0
Exp/Cntr=0.3,0.1

Type RM Length L Ch R = 1 ,9408    ,136.9,134.4,131.8
XS GIS Cut Line= 3
2442654.95471575562660.9693676032442372.98721473562526.390815759
     2441894.573      562721.661
#Sta/Elev= 30
       0 2471.54    41.6 2471.14   111.5 2467.81  140.832464.242   169.1 2457.79
   244.4 2435.74   257.7 2429.53   343.82430.581   353.9 2430.08   366.3 2427.01
   384.4 2426.27   393.9 2423.97   401.6 2422.96     406 2424.01   418.5 2430.15
   423.2 2431.08   479.8  2432.1   518.3 2430.43   544.3 2434.89   561.5 2442.18
   576.2  2450.6     622 2480.83   647.9 2494.26     670 2504.11     717 2520.52
   751.6 2523.61   777.5 2527.45   794.8 2533.65   807.7 2540.73   829.2 2546.36
#Mann= 5 ,-1 , 0
       0     .05       0  140.83     .06       0   343.8      .1       0
   393.9    .045       0     406      .1       0
#XS Ineff= 2 , 0
          374.69 2429.39
Permanent Ineff=
       F       F
Bank Sta=393.9,406
XS Rating Curve= 0 ,0
Exp/Cntr=0.3,0.1

Type RM Length L Ch R = 1 ,9273    ,123.7,127.3,130.1
XS GIS Cut Line= 3
2442568.57928681562576.0009207792442328.93450119562376.452195427
     2441874.868      562682.948
#Sta/Elev= 30
       0  2458.4      262456.102    70.5 2448.11   122.6 2435.29   138.2 2429.05
  177.362429.555   213.1 2428.22   236.32428.651  324.052425.161   358.1 2423.34
   372.8 2421.45   401.8 2421.79   413.72418.955   421.4 2417.71   428.72418.602
   441.6 2423.84   447.4  2425.1   483.8 2427.08   522.3 2426.47   527.2 2427.33
   557.8 2437.81   631.7 2466.13   686.5 2484.49   738.3 2505.19     754 2508.75
   778.2 2511.91   800.9 2516.98   815.2 2521.86   827.6 2527.55   859.7 2536.54
#Mann= 7 ,-1 , 0
       0     .05       0      26     .06       0  177.36      .1       0
   236.3      .1       0  324.05      .1       0   413.7    .045       0
   428.7      .1       0
#XS Ineff= 2 , 0
          397.12 2422.84
Permanent Ineff=
       F       F
Bank Sta=413.7,428.7
XS Rating Curve= 0 ,0
Exp/Cntr=0.3,0.1

Type RM Length L Ch R = 1 ,9146    ,94.7,92,89.1
XS GIS Cut Line= 4
2442556.42785532 562445.830083352442274.93222716562295.448784379
2442068.50730725562363.4265582862441875.46699489562676.587708079
#Sta/Elev= 30
       0 2432.21    38.6 2430.58    48.6  2428.9   77.862428.792  157.462426.868
   252.6 2425.14   288.1  2422.9   336.6 2418.11   361.8 2419.44   374.5 2417.17
  390.082417.396   408.1 2416.89   415.52414.449     425 2412.96   427.72414.422
   437.6 2421.14     446 2422.51   454.7  2422.9   483.9 2419.97   519.4 2422.42
   533.9 2421.34   558.4 2426.02   577.2 2431.51   615.5 2445.57   661.7 2460.02
   685.2  2466.9   731.8 2477.94   788.6 2497.88   826.2 2506.22   904.4  2534.6
#Mann= 6 ,-1 , 0
       0     .06       0   77.86     .05       0  157.46      .1       0
  390.08      .1       0   415.5    .045       0   427.7      .1       0
#XS Ineff= 2 , 0
          385.82 2419.68
Permanent Ineff=
       F       F
Bank Sta=415.5,427.7
XS Rating Curve= 0 ,0
Exp/Cntr=0.3,0.1

Type RM Length L Ch R = 1 ,9054    ,247.9,233.8,220.1
XS GIS Cut Line= 4
     2442228.854       561822.962442213.93897189562199.857997444
2442006.60842806562330.887776712 2441861.8315634562674.557274032
#Sta/Elev= 30
       0 2543.94    4.43 2544.08   34.46 2543.02   105.5  2540.9   143.3  2537.8
   178.7 2527.36   191.3  2522.2   203.3 2513.89   223.3  2512.2  233.232507.438
   271.4 2487.59   315.4 2459.57  332.612450.584   377.2 2427.56   403.8 2416.25
   439.4 2412.85   446.4 2411.16   452.3 2410.12   459.72411.237   471.2 2414.18
   499.7 2417.71     528 2416.66   598.5 2418.44   625.9 2423.07     678 2440.16
   751.8 2456.69   795.2 2469.74   847.9 2487.59   890.7 2497.56   995.4  2535.2
#Mann= 7 ,-1 , 0
       0     .05       0    4.43      .1       0   34.46      .1       0
  233.23      .1       0  332.61      .1       0   446.4    .045       0
   459.7      .1       0
#XS Ineff= 2 , 0
          417.46  2419.1
Permanent Ineff=
       F       F
Bank Sta=446.4,459.7
XS Rating Curve= 0 ,0
Exp/Cntr=0.3,0.1

Type RM Length L Ch R = 1 ,8820    ,111.9,116.4,125.8
XS GIS Cut Line= 4
 2442137.5303163561827.6202108642441934.41788812562162.880701946
2441966.16010543562312.2650534042441853.37168462562666.875447743
#Sta/Elev= 30
       0 2560.28   14.352559.154    44.9 2557.06    67.8 2553.01    91.8 2545.74
   164.3 2519.69     190 2508.42   202.1 2506.16   250.8 2483.15  320.722444.376
     366 2421.84   386.4 2410.17   391.1 2408.28   403.5 2407.79   415.42404.566
   423.9 2404.12   428.12404.677   440.3 2407.33   468.9 2409.78   489.1 2414.24
  525.422416.556   534.3 2416.39   563.4 2424.08   605.4 2438.31   663.8 2451.74
   693.5 2460.16   768.8 2484.42   815.2 2497.32   889.8 2524.76   916.8 2533.29
#Mann= 6 ,-1 , 0
       0      .1       0   14.35      .1       0  320.72     .12       0
   415.4    .045       0   428.1     .12       0  525.42      .1       0
Bank Sta=415.4,428.1
XS Rating Curve= 0 ,0
Exp/Cntr=0.3,0.1

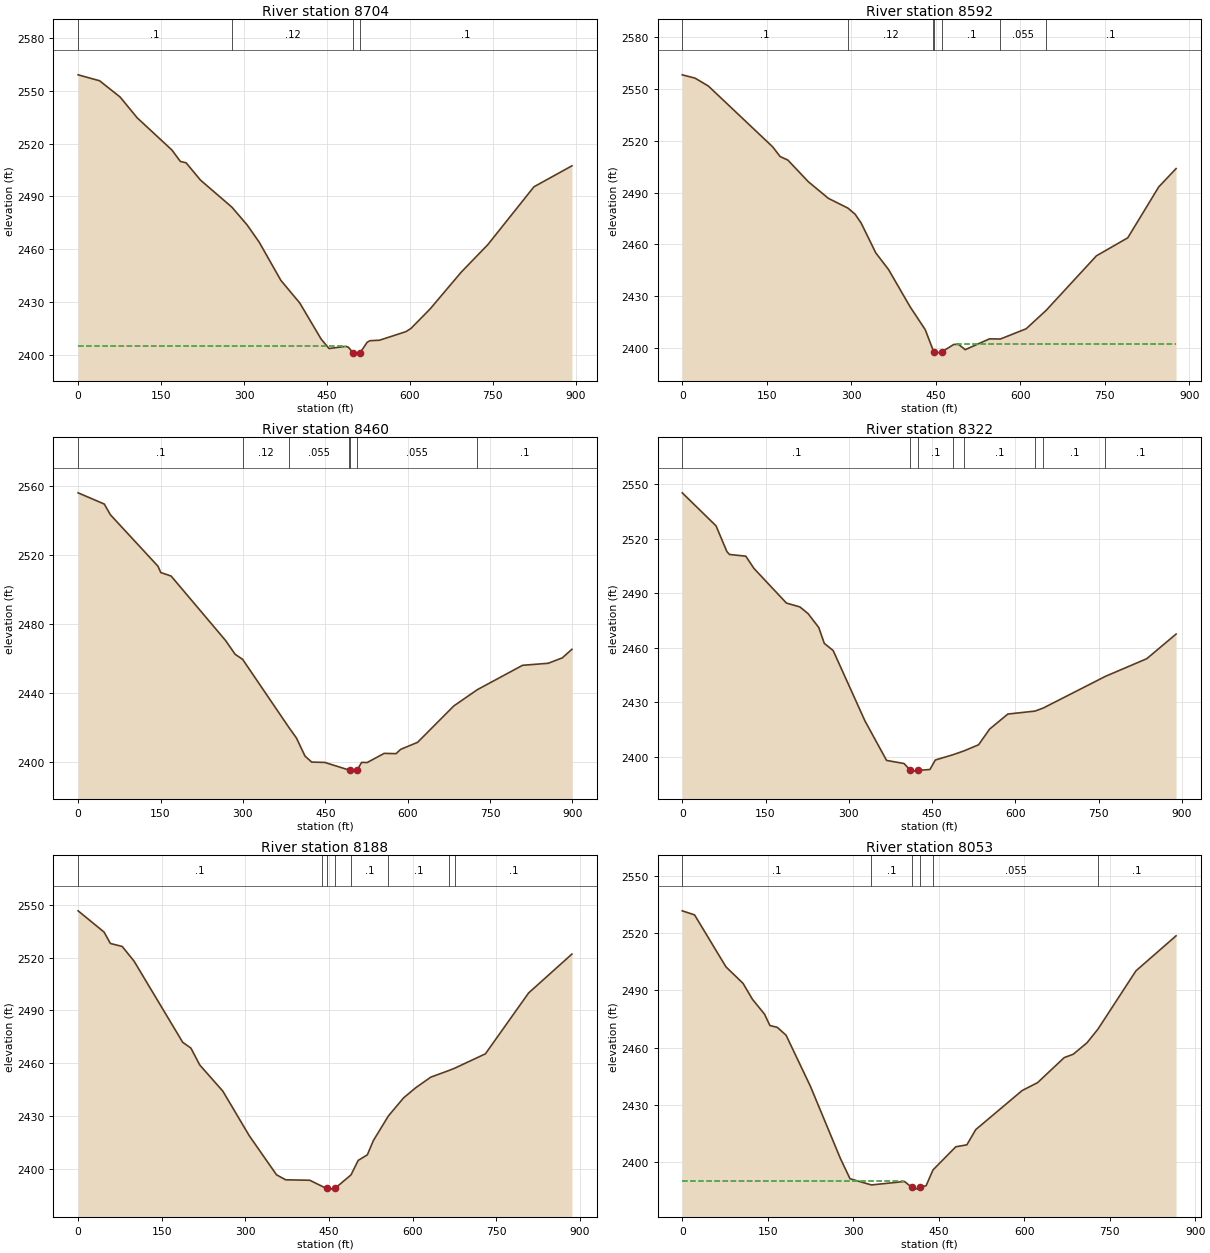
Type RM Length L Ch R = 1 ,8704    ,109.4,111.4,118.6
XS GIS Cut Line= 3
2442120.24921186561821.0940327032441921.11982814561987.633947318
2441672.14577249562570.001132845
#Sta/Elev= 30
       0 2559.11    38.9 2555.73    75.9 2546.51   106.7 2534.72   169.6 2516.37
   184.9 2509.88   195.3 2509.09   221.4 2499.23  278.282483.813   305.8 2473.69
   327.5 2463.94   366.7 2442.22   400.7 2429.44   439.4  2408.9   453.7  2403.5
   484.1 2404.74   488.5 2404.28   497.2 2401.13   504.3 2400.89   510.2 2401.22
   522.5 2406.99   527.6 2407.96     545 2408.23   592.6 2413.09   601.8 2414.92
   636.4 2425.98   692.9 2446.99   740.8 2462.55   824.2 2495.45   892.9 2507.38
#Mann= 4 ,-1 , 0
       0      .1       0  278.28     .12       0   497.2    .045       0
   510.2      .1       0
#XS Ineff= 2 , 0
           481.8 2404.84
Permanent Ineff=
       F       F
Bank Sta=497.2,510.2
XS Rating Curve= 0 ,0
Exp/Cntr=0.3,0.1

Type RM Length L Ch R = 1 ,8592    ,130,131.9,130.8
XS GIS Cut Line= 2
2442100.68967235561810.897290879     2441454.166      562402.882
#Sta/Elev= 30
       0 2558.09    22.6 2556.19    46.3 2551.63   160.4 2516.47   173.8 2510.81
   187.5 2508.76   223.9 2496.22   259.5 2486.61  294.052480.988   306.8 2477.48
   317.6 2472.32   343.6 2455.04   366.3 2445.39   404.4 2423.93   431.4 2410.62
  445.982398.211   447.22397.654   451.2 2397.07   461.62397.998   482.3 2402.13
   490.8 2402.08   502.3 2399.06   545.4 2405.33  564.762405.246   610.5 2411.16
  646.062421.845   735.2 2453.36   790.9  2463.8   845.8 2493.23   876.6 2503.84
#Mann= 7 ,-1 , 0
       0      .1       0  294.05     .12       0  445.98      .1       0
   447.2    .045       0   461.6      .1       0  564.76    .055       0
  646.06      .1       0
#XS Ineff= 2 , 0
                          485.46         2402.57
Permanent Ineff=
       F       F
Bank Sta=447.2,461.6
XS Rating Curve= 0 ,0
Exp/Cntr(USF)=0,0
Exp/Cntr=0.3,0.1

Type RM Length L Ch R = 1 ,8460    ,136.3,138.9,137.7
XS GIS Cut Line= 2
2442047.37930246561732.9821348772441348.91219277562298.995125331
#Sta/Elev= 30
       0 2556.28    47.6 2549.77      59 2543.47   145.4 2513.65   150.5 2509.97
   169.3 2507.96   268.7 2470.42   285.9 2462.48  299.442459.599  383.48 2420.14
   397.6 2413.81   413.1 2403.36   425.2  2399.9   449.1 2399.69  493.38 2395.26
   495.4 2395.16   504.8 2394.64   507.7 2395.13   516.2 2399.72   526.3 2399.64
   557.2 2404.96   578.8 2404.79   587.3 2407.29   618.1 2411.38     684 2432.51
  726.872441.969   809.1  2456.1   855.8 2457.28   881.5 2460.42     899 2465.41
#Mann= 7 ,-1 , 0
       0      .1       0  299.44     .12       0  383.48    .055       0
  493.38      .1       0   495.4    .045       0   507.7    .055       0
  726.87      .1       0
Bank Sta=495.4,507.7
XS Rating Curve= 0 ,0
Exp/Cntr=0.3,0.1

Type RM Length L Ch R = 1 ,8322    ,133.9,133.1,130.5
XS GIS Cut Line= 3
2441964.33913488561681.5132138942441523.84872408561988.916501326
2441342.77135832562291.312672353
#Sta/Elev= 30
       0 2545.27    60.9 2527.08    80.4 2512.92    85.1 2511.32   114.5 2510.37
   129.1 2503.65   187.7 2484.54     212 2482.41   226.7 2478.73     246 2471.04
   255.9 2462.34   271.9 2458.38   329.1 2419.66   368.1 2397.86   399.5 2396.16
   410.82392.508   415.5 2391.96   425.42392.403   446.2 2392.85   455.9 2398.09
  487.192400.942  507.882403.139   533.9  2406.5   553.6 2415.08   586.5  2423.4
  635.422425.029  650.342426.718  762.262444.156   836.9 2453.91   889.6 2467.46
#Mann= 8 ,-1 , 0
       0      .1       0   410.8    .045       0   425.4      .1       0
  487.19    .055       0  507.88      .1       0  635.42    .055       0
  650.34      .1       0  762.26      .1       0
Bank Sta=410.8,425.4
XS Rating Curve= 0 ,0
Exp/Cntr=0.3,0.1

Type RM Length L Ch R = 1 ,8188    ,132.5,135,137
XS GIS Cut Line= 2
 2441848.7102466561542.6296743862441196.13022547562141.456606947
#Sta/Elev= 30
       0 2546.55    46.5 2534.49    57.9 2527.99    79.1 2526.29   100.4 2517.93
   187.6 2471.79   202.3 2468.52   218.2  2458.9   259.6 2444.02     307 2418.67
   355.9 2396.45   372.2 2393.62   415.6 2393.35  437.732389.899   445.7 2388.67
   453.6 2388.31   460.7 2388.73  489.45  2396.4   502.3 2404.63   518.8 2407.83
   529.6 2415.94   556.62429.961   583.9 2440.24   605.6 2445.98   632.5 2451.97
  665.172455.772  675.472457.077   730.5 2465.23     808 2499.85   885.7 2521.96
#Mann= 8 ,-1 , 0
       0      .1       0  437.73      .1       0   445.7    .045       0
   460.7      .1       0  489.45      .1       0   556.6      .1       0
  665.17    .055       0  675.47      .1       0
Bank Sta=445.7,460.7
XS Rating Curve= 0 ,0
Exp/Cntr=0.3,0.1

Type RM Length L Ch R = 1 ,8053    ,120.6,120.1,119.2
XS GIS Cut Line= 3
      2441784.72      561522.4932441366.65147952561785.243549672
2441180.21961649 562107.94391895
#Sta/Elev= 30
       0 2531.88    21.6 2529.75    76.8 2502.38   106.6 2493.77   123.2 2485.35
   144.4 2477.54   153.8 2471.57   166.8  2470.6   182.2 2466.47   224.8 2439.68
   277.5 2401.65   294.4 2390.98  332.052387.724   390.1 2389.53   402.6 2386.47
   408.9 2385.52   417.72386.436   427.9  2387.3  439.892395.591     480 2407.79
   499.4 2408.82     515 2416.82   596.4 2437.37   623.4  2441.5   670.3  2454.7
     686 2456.45     710 2462.42  729.412469.644   796.1 2500.32   866.5 2518.74
#Mann= 6 ,-1 , 0
       0      .1       0  332.05      .1       0   402.6    .045       0
   417.7      .1       0  439.89    .055       0  729.41      .1       0
#XS Ineff= 2 , 0
          387.59 2389.66
Permanent Ineff=
       F       F
Bank Sta=402.6,417.7
XS Rating Curve= 0 ,0
Exp/Cntr=0.3,0.1

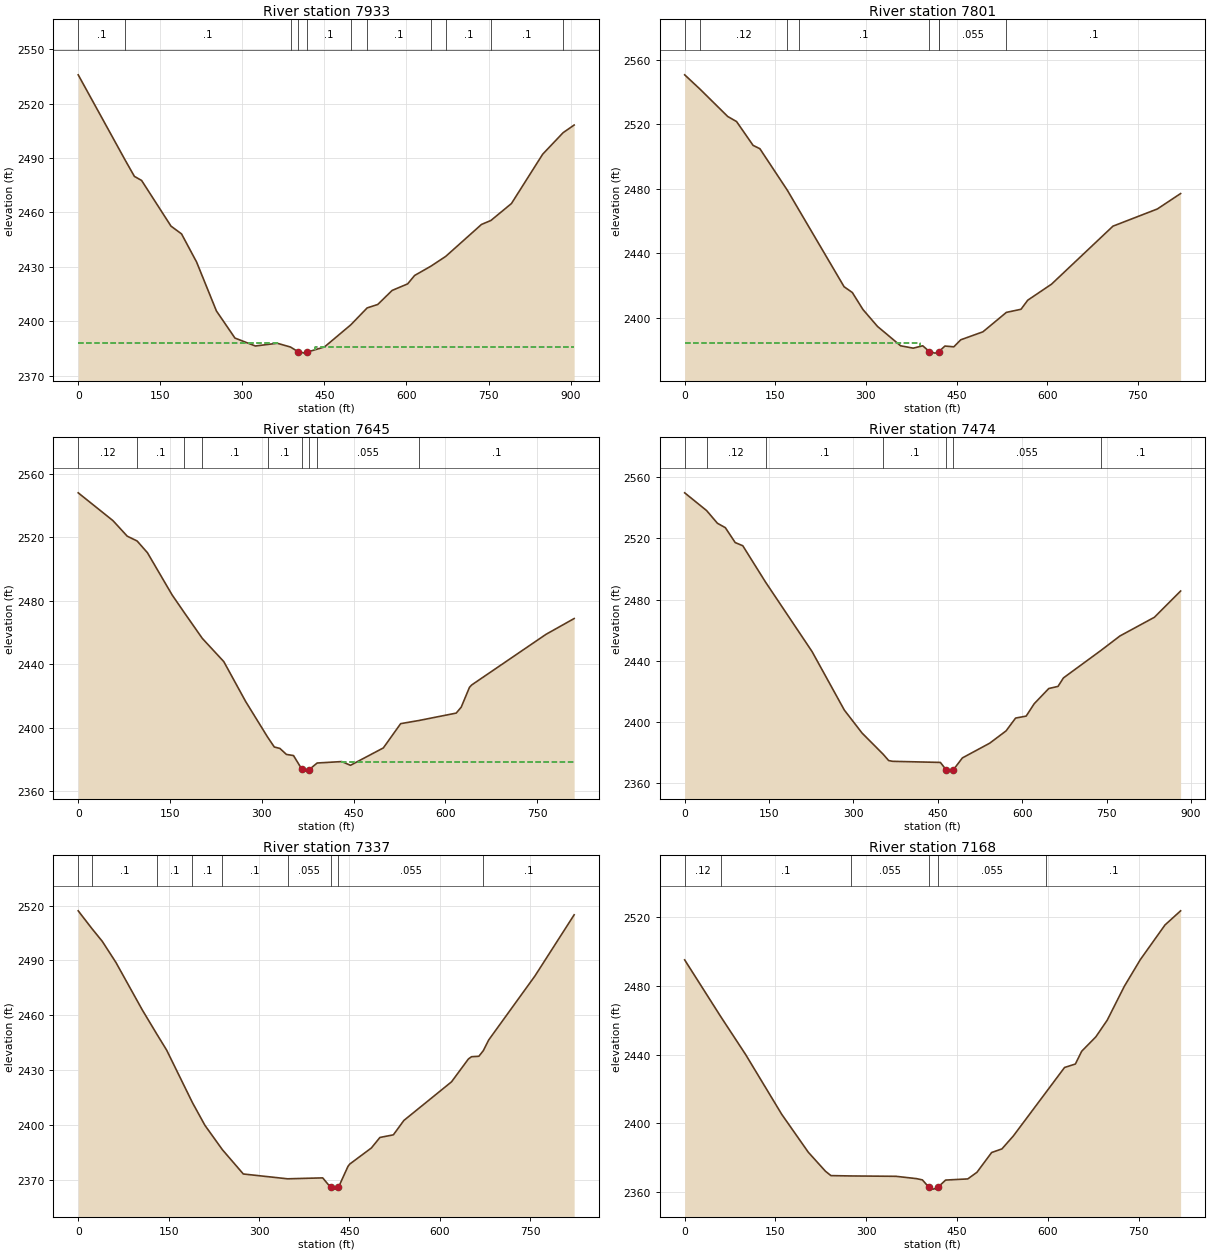
Type RM Length L Ch R = 1 ,7933    ,132.9,131.9,130.2
XS GIS Cut Line= 3
2441709.41359537561406.0663930532441265.49846997561716.896921601
2441150.70593053562062.933491162
#Sta/Elev= 30
       0 2535.82   85.842488.794   102.7 2479.83   115.9 2477.57   169.6  2452.4
   188.9  2448.1   216.4 2432.59   252.6 2405.64   286.5 2390.67   323.8 2386.31
     364  2387.8  388.062385.724   401.4 2383.23   413.7 2382.37   418.6 2382.93
   450.2 2385.79  498.362398.007   528.1 2407.29   547.5  2409.2   573.8 2416.94
   602.2 2420.56   614.8 2425.17  644.712430.322   671.82435.718   737.1 2453.32
  754.342455.508   791.9 2464.86     849 2492.06  886.442503.952   906.5 2508.14
#Mann= 11 ,-1 , 0
       0      .1       0   85.84      .1       0  388.06      .1       0
   401.4    .045       0   418.6      .1       0  498.36      .1       0
   528.1      .1       0  644.71    .055       0   671.8      .1       0
  754.34      .1       0  886.44      .1       0
#XS Ineff= 2 , 0
          364.62 2387.96  433.32         2385.54
Permanent Ineff=
       F       F
Bank Sta=401.4,418.6
XS Rating Curve= 0 ,0
Exp/Cntr=0.3,0.1

Type RM Length L Ch R = 1 ,7801    ,156.5,156.3,154.8
XS GIS Cut Line= 3
2441546.08976498561231.1872254732441398.09092843 561448.97813956
2440973.19192098561810.067651229
#Sta/Elev= 30
       0 2550.74   25.532541.809    71.3  2524.9    85.9 2521.77   113.2 2507.03
   124.5 2504.93  170.062479.135  189.062467.018   263.9 2419.37   277.5  2415.8
   295.1 2405.26   319.2 2394.77   357.5 2382.77   378.3 2381.31     394 2382.79
   405.12379.198   414.3 2378.23   420.3 2379.03  420.532379.121   430.8 2382.62
   445.5 2382.14     457  2386.5   493.7 2391.44  532.512403.492   556.7 2405.41
   567.8 2411.02   607.2 2420.97   708.9 2456.93   782.4 2467.59   820.9 2477.15
#Mann= 8 ,-1 , 0
       0      .1       0   25.53     .12       0  170.06      .1       0
  189.06      .1       0   405.1    .045       0   420.3      .1       0
  420.53    .055       0  532.51      .1       0
#XS Ineff= 2 , 0
          389.65 2384.66  431.51          2381.9
Permanent Ineff=
       F       F
Bank Sta=405.1,420.3
XS Rating Curve= 0 ,0
Exp/Cntr=0.3,0.1

Type RM Length L Ch R = 1 ,7645    ,172.6,171.3,168.9
XS GIS Cut Line= 3
2441515.50232358561212.4345701792441241.67023502561373.556079017
2440901.38807902561729.903011578
#Sta/Elev= 30
       0 2548.06    56.9  2530.5    80.1 2520.75   96.222517.731   113.1 2510.35
   153.3 2483.84  173.282472.631  202.79 2456.36   237.9 2441.73   273.7 2416.55
  309.362394.263   320.4 2387.95   329.6 2387.04   340.2 2383.27   351.8 2382.55
   365.7  2373.8   371.3 2372.74   377.62373.745  390.432377.857   430.7 2378.76
   444.9 2376.41   498.6 2387.36   526.9 2402.65  557.042404.655   617.7  2409.3
   625.9 2413.07   639.3 2425.49   642.9    2427   764.5 2458.94   810.4 2468.86
#Mann= 9 ,-1 , 0
       0     .12       0   96.22      .1       0  173.28      .1       0
  202.79      .1       0  309.36      .1       0   365.7    .045       0
   377.6      .1       0  390.43    .055       0  557.04      .1       0
#XS Ineff= 2 , 0
                          429.72         2378.76
Permanent Ineff=
       F       F
Bank Sta=365.7,377.6
XS Rating Curve= 0 ,0
Exp/Cntr=0.3,0.1

Type RM Length L Ch R = 1 ,7474    ,131.8,137.1,141
XS GIS Cut Line= 3
2441442.07569801561088.1910234722441125.76758592561253.506783275
     2440828.111      561685.682
#Sta/Elev= 30
       0 2549.83   39.072538.209    58.2 2529.94    72.3 2527.06    89.8 2517.34
   103.3 2515.25  143.73 2491.51   226.5 2446.07   283.8 2407.87   315.4 2392.82
  353.052378.922   362.6 2374.87   369.7 2374.36   454.6 2373.64   464.6 2368.93
   469.4 2367.95   477.6 2368.78   493.7 2376.58   542.3 2386.21   571.4 2394.25
   588.3 2402.62   607.1 2403.91   621.4 2411.99   647.3 2421.94   663.7 2423.32
   673.4 2428.88  739.712446.722   773.8 2456.28   835.1  2468.5   881.7 2485.66
#Mann= 7 ,-1 , 0
       0      .1       0   39.07     .12       0  143.73      .1       0
  353.05      .1       0   464.6    .045       0   477.6    .055       0
  739.71      .1       0
Bank Sta=464.6,477.6
XS Rating Curve= 0 ,0
Exp/Cntr=0.3,0.1

Type RM Length L Ch R = 1 ,7337    ,167.9,168.3,168.1
XS GIS Cut Line= 2
2441316.09223267  561033.18918622440623.19623267  561477.3181862
#Sta/Elev= 30
       0  2517.1   22.722507.406    39.9 2500.45    62.7 2488.83   106.4 2462.91
  130.972449.453   146.7 2441.02  189.552412.293   210.3 2399.88  239.232386.576
     274 2373.29  347.492370.655   405.7 2371.17   418.8 2366.01   427.5 2365.02
   431.8 2365.96   447.7 2377.47   450.6 2378.71   486.5 2387.51   500.7 2393.26
     523 2394.69   540.4 2402.54   619.5 2423.65   647.5 2436.14   652.7 2437.38
   664.9 2437.62  672.262440.697   681.2 2446.53   757.9 2481.49     823 2514.92
#Mann= 9 ,-1 , 0
       0     .12       0   22.72      .1       0  130.97      .1       0
  189.55      .1       0  239.23      .1       0  347.49    .055       0
   418.8    .045       0   431.8    .055       0  672.26      .1       0
Bank Sta=418.8,431.8
XS Rating Curve= 0 ,0
Exp/Cntr=0.3,0.1

Type RM Length L Ch R = 1 ,7168    ,129.3,130.7,131.7
XS GIS Cut Line= 2
 2441228.2413023560899.146418557 2440531.5103023561330.664418557
#Sta/Elev= 30
       0 2495.13   59.442462.182   100.8 2439.98   160.4  2405.2   204.3 2383.12
   232.6 2372.08   241.7 2369.52  274.542369.324   349.2 2369.11   383.1 2367.76
   392.8 2367.02   403.32362.851   411.3 2361.65   418.32362.712   431.2 2366.92
   467.8  2367.6   482.9 2371.43   507.2 2382.96   524.2 2385.07   543.1 2392.61
  597.192418.099   627.7 2432.48   645.6  2434.5     656 2441.92   679.5 2450.35
   698.3 2460.08   726.5 2479.76     753 2495.33   793.7 2515.47   819.5  2523.7
#Mann= 6 ,-1 , 0
       0     .12       0   59.44      .1       0  274.54    .055       0
   403.3    .045       0   418.3    .055       0  597.19      .1       0
Bank Sta=403.3,418.3
XS Rating Curve= 0 ,0
Exp/Cntr=0.3,0.1

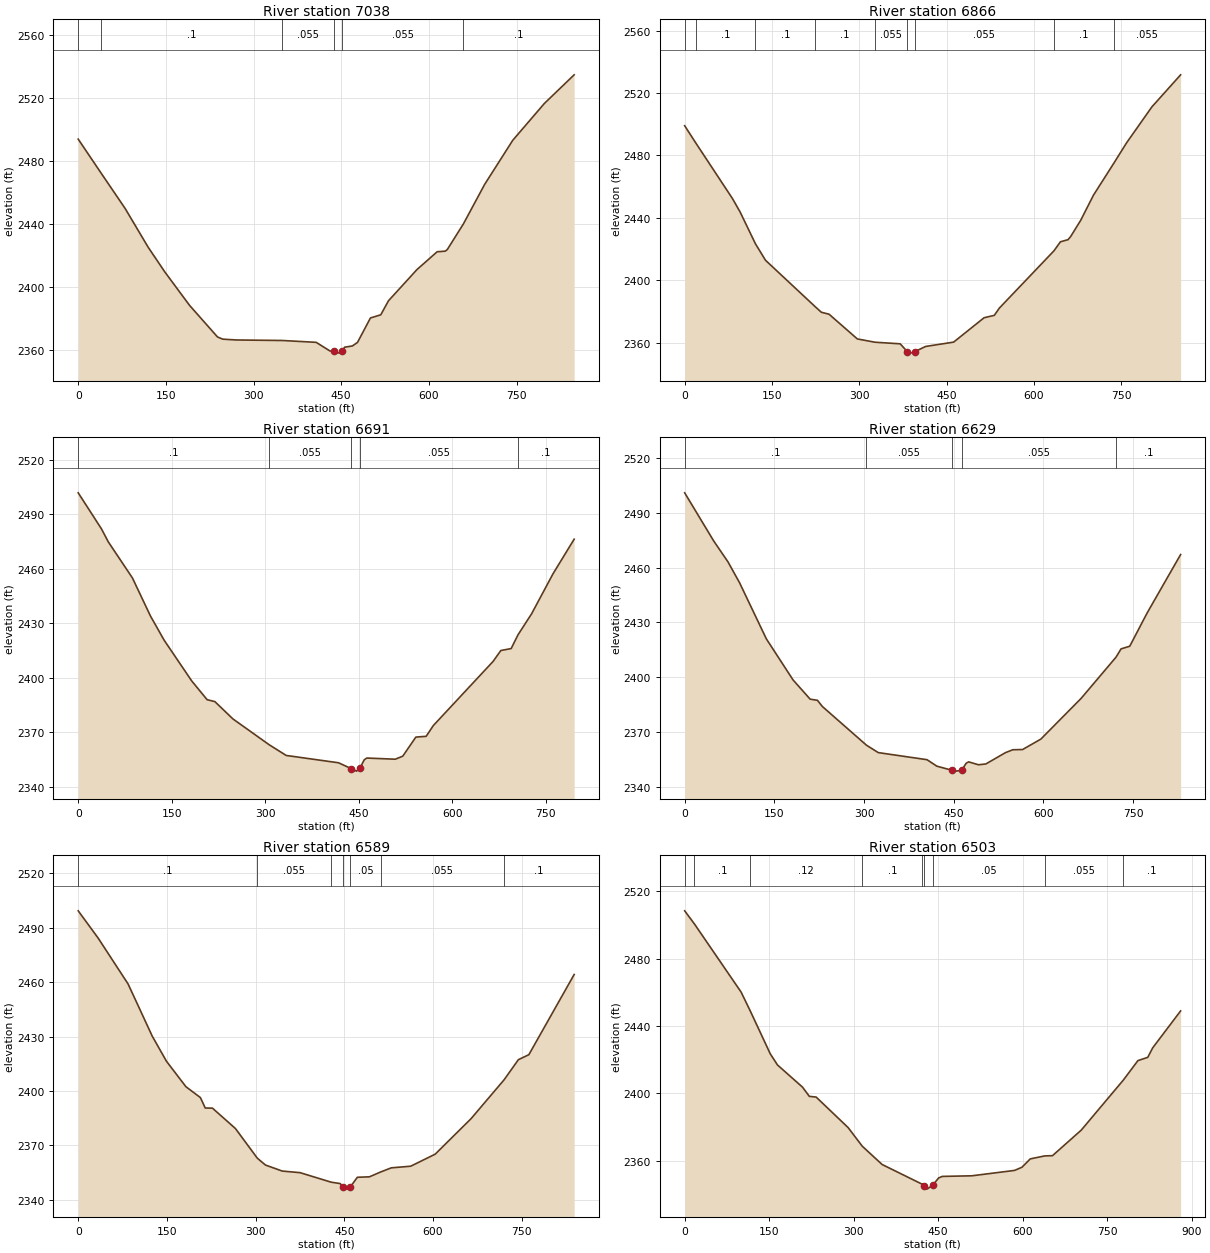
Type RM Length L Ch R = 1 ,7038    ,169.8,171.3,170.7
XS GIS Cut Line= 2
2441199.06794414560825.5667649812440431.11097684 561186.52744688
#Sta/Elev= 30
       0 2493.75   39.392472.084    80.2 2449.81   119.9 2425.04   148.2 2409.48
   190.6 2388.23   238.4  2368.2   247.4 2366.82   270.2  2366.3   349.3 2365.97
   407.2 2364.79   430.8 2359.32   438.1 2359.05     447 2357.95   451.4 2359.31
   455.8  2361.7   469.1  2362.5   477.9 2364.75     500 2380.26   517.7 2382.27
   530.9 2391.17   579.5 2410.93   614.2 2422.29   628.2 2422.67   631.6 2423.72
  659.212440.029   695.4    2465   743.5    2493   797.6 2516.38   848.6 2534.57
#Mann= 6 ,-1 , 0
       0     .12       0   39.39      .1       0   349.3    .055       0
   438.1    .045       0   451.4    .055       0  659.21      .1       0
Bank Sta=438.1,451.4
XS Rating Curve= 0 ,0
Exp/Cntr=0.3,0.1

Type RM Length L Ch R = 1 ,6866    ,172.8,175.5,176.9
XS GIS Cut Line= 2
2441157.65314646560691.2986743862440377.45320232 561034.43316758
#Sta/Elev= 30
       0 2499.03    19.12487.988    82.1 2452.35    95.2 2443.77   121.72423.282
   138.9 2412.77  224.292382.991     235  2379.4   248.1 2378.18   296.7 2362.32
  326.892360.214   370.4 2359.18   382.5  2354.2   387.9 2353.21   395.12354.081
   414.1 2357.49   462.2 2360.27   514.6 2375.91   532.1 2377.43   540.8 2382.09
  634.692418.841   645.7 2424.58   658.8 2425.97   663.2 2427.89   680.7 2438.46
   702.5 2454.49  737.292474.871   759.3    2488     803 2511.16   852.3 2531.68
#Mann= 9 ,-1 , 0
       0      .1       0    19.1      .1       0   121.7      .1       0
  224.29      .1       0  326.89    .055       0   382.5    .045       0
   395.1    .055       0  634.69      .1       0  737.29    .055       0
Bank Sta=382.5,395.1
XS Rating Curve= 0 ,0
Exp/Cntr=0.3,0.1

Type RM Length L Ch R = 1 ,6691    ,56.2,62.4,68.4
XS GIS Cut Line= 2
     2441130.689      560595.5472440360.77485787560795.800030666
#Sta/Elev= 30
       0 2501.69    37.4 2481.82    48.3 2474.72      87 2454.88   115.9 2433.98
   137.9 2420.66     182 2398.33   206.8 2387.98   219.2 2386.94   248.1 2377.43
  306.492363.185   333.6 2357.34   417.6 2353.31   437.82350.122   446.5 2348.72
   451.7 2350.29   458.9 2354.99     463 2355.91   508.5 2355.27   520.6 2356.94
   541.6 2367.43   558.1 2367.85   569.7  2373.8   665.5 2409.03   677.9 2415.02
   694.5 2416.09  705.512423.693   727.2 2435.17   761.6 2457.19   795.5 2476.21
#Mann= 5 ,-1 , 0
       0      .1       0  306.49    .055       0   437.8    .045       0
   451.7    .055       0  705.51      .1       0
Bank Sta=437.8,451.7
XS Rating Curve= 0 ,0
Exp/Cntr=0.5,0.3

Type RM Length L Ch R = 1 ,6629    ,41,39.9,39.9
XS GIS Cut Line= 4
2441128.79856126 560591.884111722440748.67550466560663.379420352
2440565.99552996560622.0293814742440337.47524795 560736.35913321
#Sta/Elev= 30
       0 2500.86    48.5 2474.58    72.5 2463.09    91.9 2451.65   136.6 2421.04
   181.4 2398.53   209.9 2388.06   222.1 2387.44   230.2 2384.09  303.962362.934
   323.8 2358.85   405.4 2354.97   421.8 2351.43   447.7 2349.14   454.6 2348.72
   463.52349.283     471 2353.07   475.1 2353.78   491.5  2352.2   503.8 2352.64
   536.6 2358.82   548.9  2360.4   565.3 2360.53   595.8 2366.22   663.3 2388.53
  721.582411.034     730 2415.56   744.5    2417   773.5 2435.12   829.6 2467.13
#Mann= 5 ,-1 , 0
       0      .1       0  303.96    .055       0   447.7    .045       0
   463.5    .055       0  721.58      .1       0
#XS Ineff= 2 , 0
          415.14 2352.14  472.53          2352.9
Permanent Ineff=
       F       F
Bank Sta=447.7,463.5
XS Rating Curve= 0 ,0
Exp/Cntr=0.5,0.3

Type RM Length L Ch R = 1 ,6589    ,84.6,85.4,86.4
XS GIS Cut Line= 4
     2441121.407       560553.612440751.40936978560625.105308632
2440568.72939509560583.7552697542440321.64583138560703.147734681
#Sta/Elev= 30
       0 2499.28    33.8 2484.22    84.4 2458.94   125.1 2430.28   149.2  2416.4
   182.2 2402.33   206.6 2396.38   214.8 2390.61     227 2390.54   265.9  2379.3
  302.842362.974   316.6 2359.19   345.1 2355.86   375.1 2354.99  427.562349.756
   443.1 2348.96   447.4 2347.29   455.6 2345.91   460.2 2347.15     472 2352.44
   492.5  2352.7  511.262355.334   529.4 2357.64   562.2 2358.54   603.6 2365.17
   664.3 2384.74  720.232406.197   744.3 2417.25     762 2419.99   838.6 2464.18
#Mann= 7 ,-1 , 0
       0      .1       0  302.84    .055       0  427.56     .05       0
   447.4    .045       0   460.2     .05       0  511.26    .055       0
  720.23      .1       0
Bank Sta=447.4,460.2
XS Rating Curve= 0 ,0
Exp/Cntr(USF)=0,0
Exp/Cntr=0.5,0.3

Type RM Length L Ch R = 1 ,6503    ,101,97.7,93
XS GIS Cut Line= 4
2441125.75677785560502.1795971012440773.05442558560551.119157943
2440562.10804264560483.6163154032440285.34638823560606.809003038
#Sta/Elev= 30
       0 2508.44   17.282500.663   100.2 2460.14  116.622448.813   151.9 2423.49
   164.8 2416.82   209.2 2403.65   221.3 2398.17   233.4 2397.75   290.2  2379.6
  315.31 2368.54   350.5 2357.68  421.772345.935   424.82345.033   430.1 2343.03
     4402345.274     451  2349.7   457.4 2350.59   509.9 2350.95   585.8 2354.16
   598.9 2356.06   613.6 2361.01  639.382362.775     653 2362.91     704 2378.07
  778.96 2407.91   804.7 2419.42   822.2 2421.37     831 2427.04   880.5 2448.95
#Mann= 9 ,-1 , 0
       0     .12       0   17.28      .1       0  116.62     .12       0
  315.31      .1       0  421.77     .05       0   424.8    .045       0
     440     .05       0  639.38    .055       0  778.96      .1       0
Bank Sta=424.8,440
XS Rating Curve= 0 ,0
Exp/Cntr(USF)=0,0
Exp/Cntr=0.3,0.1

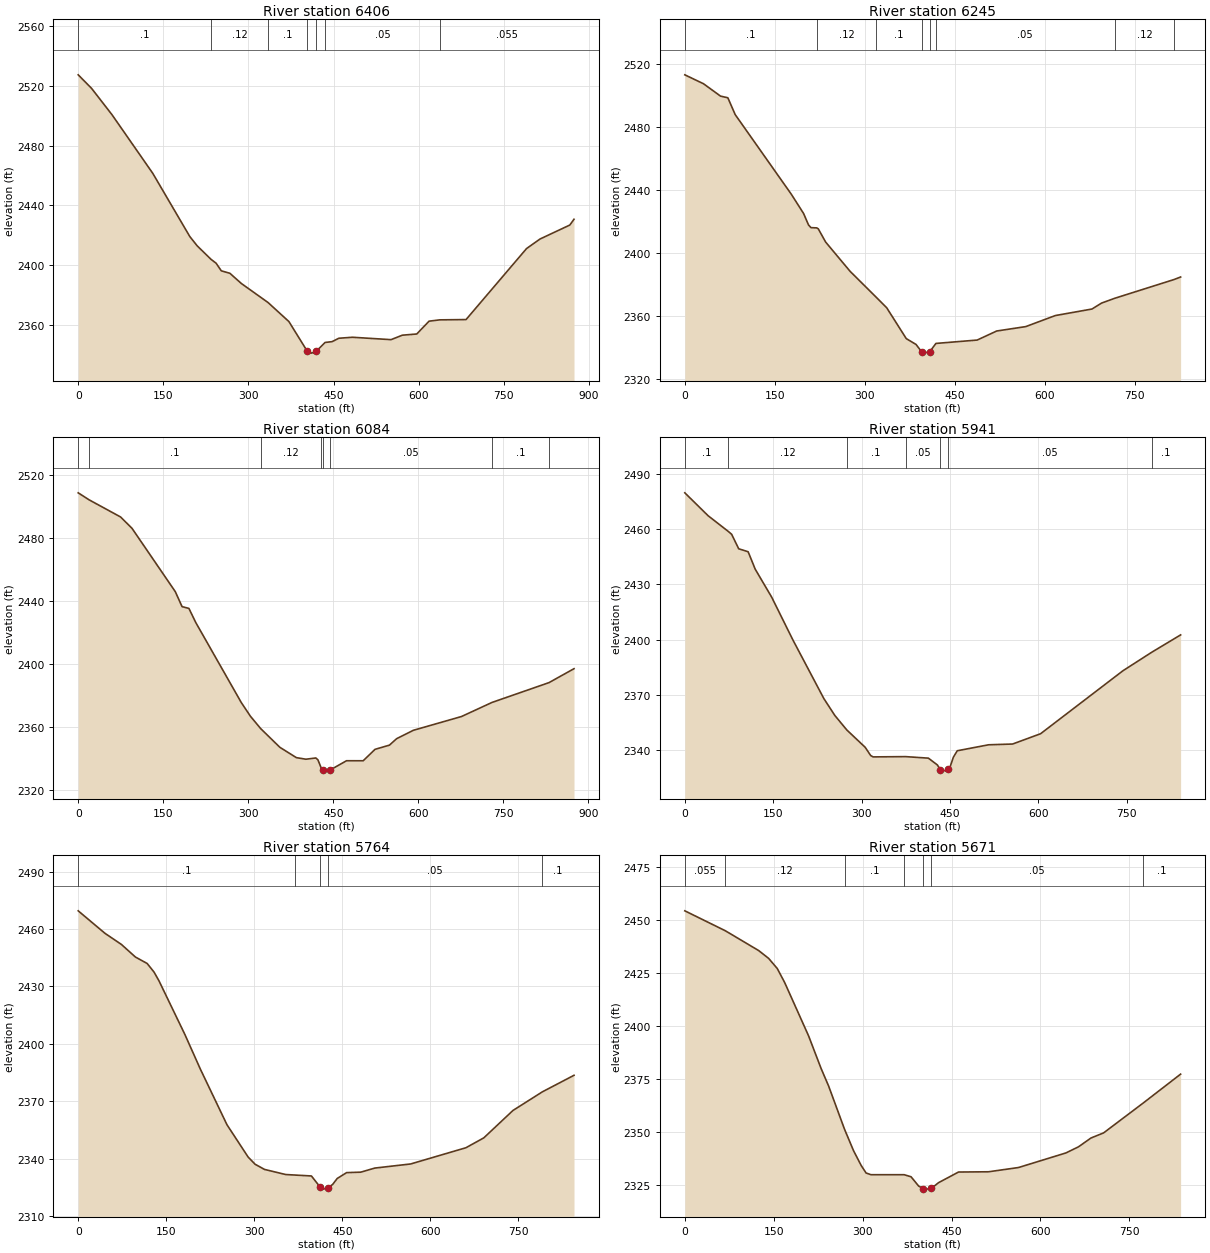
Type RM Length L Ch R = 1 ,6406    ,162.9,161,157.7
XS GIS Cut Line= 4
2441121.29174417560368.1769998432440874.80028645560434.183775391
2440549.77409962560434.183775391 2440279.3533023560548.737790958
#Sta/Elev= 30
       0 2527.43    23.6 2518.34    59.5 2500.74   131.4 2461.45   196.7 2419.09
   209.7 2412.86  234.142403.802     243 2401.25   252.2 2396.13   267.4 2394.45
   287.5 2387.64  334.592374.876   371.4 2362.11   403.4 2342.46   411.4 2340.97
   419.5 2342.21   435.22348.123   447.4 2348.65   459.4 2350.94   483.4  2351.6
   551.4    2350   571.4    2353   596.7 2353.78   618.4 2362.38  637.342363.259
   683.6 2363.45   790.2 2411.01   813.9 2417.41   866.5 2426.79   873.9 2430.67
#Mann= 7 ,-1 , 0
       0      .1       0  234.14     .12       0  334.59      .1       0
   403.4    .045       0   419.5      .1       0   435.2     .05       0
  637.34    .055       0
Bank Sta=403.4,419.5
XS Rating Curve= 0 ,0
Exp/Cntr=0.3,0.1

Type RM Length L Ch R = 1 ,6245    ,161.2,160.2,158
XS GIS Cut Line= 2
2441081.02667439560201.5006510712440269.50167439560359.747651071
#Sta/Elev= 30
       0 2513.21    31.1 2507.56    59.6 2499.68    71.8 2498.63      84 2487.96
   177.8 2437.26   198.1 2425.12   206.3 2417.86   210.4 2416.15  219.992415.998
   222.6 2415.38   234.8 2407.02   275.6 2388.43  319.362371.882   336.7 2365.26
   369.3 2345.68   385.6 2341.97     395 2337.27   397.8 2336.46   408.6 2337.42
  418.732342.614   487.5 2344.76   520.1 2350.51   568.5  2353.3   617.9 2360.33
     679 2364.47     695 2368.25  716.832371.278   816.22383.243   826.8 2384.81
#Mann= 8 ,-1 , 0
       0      .1       0  219.99     .12       0  319.36      .1       0
     395    .045       0   408.6      .1       0  418.73     .05       0
  716.83     .12       0   816.2      .1       0
Bank Sta=395,408.6
XS Rating Curve= 0 ,0
Exp/Cntr=0.3,0.1

Type RM Length L Ch R = 1 ,6084    ,141.9,143.5,144.5
XS GIS Cut Line= 3
2441068.98420936560142.8120699432440704.69312325560109.157588562
2440221.09383711560267.240255671
#Sta/Elev= 30
       0 2508.88   19.372504.396    74.8 2493.51    94.9 2486.31   171.2 2446.06
   183.2  2436.5   195.3 2435.36   207.3 2426.43   287.6 2375.53   303.7 2366.81
   321.92358.906   355.7 2347.02   384.9 2340.43   401.7 2339.44   419.2 2340.23
   422.8 2339.07  428.412334.085   431.2 2332.42   435.4 2331.86   444.6 2332.62
   473.3 2338.46   502.7 2338.45   523.6 2345.72     549 2348.39   561.6 2352.47
   591.1 2357.82   676.1 2366.59  729.992375.559  830.512388.158   874.6 2397.02
#Mann= 8 ,-1 , 0
       0    .055       0   19.37      .1       0   321.9     .12       0
  428.41     .05       0   431.2    .045       0   444.6     .05       0
  729.99      .1       0  830.51      .1       0
Bank Sta=431.2,444.6
XS Rating Curve= 0 ,0
Exp/Cntr=0.3,0.1

Type RM Length L Ch R = 1 ,5941    ,174.3,176.7,179.2
XS GIS Cut Line= 4
2440998.00365123559985.0254653432440686.46735576 559987.65247199
2440443.45712262560037.7733325752440208.04020936560193.061139572
#Sta/Elev= 30
       0 2479.84    39.5  2467.4   74.122458.763    79.5 2457.28    91.5  2449.4
   107.5  2447.8   119.5 2438.32   147.5 2423.07   183.2 2399.99   236.1 2367.89
   254.6 2358.78  275.082350.828   306.2 2341.43   315.5 2336.96   319.6  2336.2
  374.882336.344   413.5 2335.52   428.8 2331.81     434 2329.15     438 2328.46
   447.52329.386   450.3 2330.73   455.9 2336.02   462.5 2339.54   515.6 2342.78
   556.5  2343.2     604 2348.81   743.7 2383.04   792.82393.149   841.7 2402.56
#Mann= 7 ,-1 , 0
       0      .1       0   74.12     .12       0  275.08      .1       0
  374.88     .05       0     434    .045       0   447.5     .05       0
   792.8      .1       0
Bank Sta=434,447.5
XS Rating Curve= 0 ,0
Exp/Cntr=0.3,0.1

Type RM Length L Ch R = 1 ,5764    ,96.9,92.9,89.3
XS GIS Cut Line= 3
2440968.01125583559843.2625581292440461.68289011559838.808704189
2440174.25234893560017.782465343
#Sta/Elev= 30
       0 2469.48    45.5 2457.75    73.5 2451.94    97.5 2445.33   117.5 2441.96
   129.2 2437.47   137.5 2432.99   181.5 2405.04   208.5 2386.53   253.5 2357.68
   289.5 2340.82   301.5 2337.01   317.5 2334.32   353.4 2331.66   369.62331.367
   397.4  2330.9   412.72324.939   417.4 2324.02   425.4 2324.75   433.4  2326.4
   441.4 2329.59   457.4 2332.65   481.4 2332.88   505.4 2335.02   566.5 2337.17
   660.8 2345.66   691.2 2350.82   740.9 2365.14  790.872374.851   844.9 2383.52
#Mann= 5 ,-1 , 0
       0      .1       0   369.6     .05       0   412.7    .045       0
   425.4     .05       0  790.87      .1       0
Bank Sta=412.7,425.4
XS Rating Curve= 0 ,0
Exp/Cntr=0.3,0.1

Type RM Length L Ch R = 1 ,5671    ,161.9,160.3,157.7
XS GIS Cut Line= 2
2440932.72388374559619.2773256142440139.09288374559883.651325614
#Sta/Elev= 30
       0 2454.26   68.242444.868   124.6  2435.5   141.4 2431.81     156 2427.02
   168.6 2420.33   208.9 2395.17   229.9 2379.83   242.6 2371.55  269.482351.111
   284.7 2340.99   297.4  2334.1   305.8 2330.47   314.1 2329.66  370.092329.657
   381.7 2328.69   394.4 2324.33   402.22323.082   408.9 2322.85   415.8 2323.16
   428.1  2325.9   461.8 2330.92   512.4 2331.04     563 2333.05   643.1 2339.95
   664.2 2342.83   685.2 2346.98   706.6 2349.41  772.562363.332   836.5 2377.15
#Mann= 7 ,-1 , 0
       0    .055       0   68.24     .12       0  269.48      .1       0
  370.09     .05       0   402.2    .045       0   415.8     .05       0
  772.56      .1       0
Bank Sta=402.2,415.8
XS Rating Curve= 0 ,0
Exp/Cntr=0.3,0.1