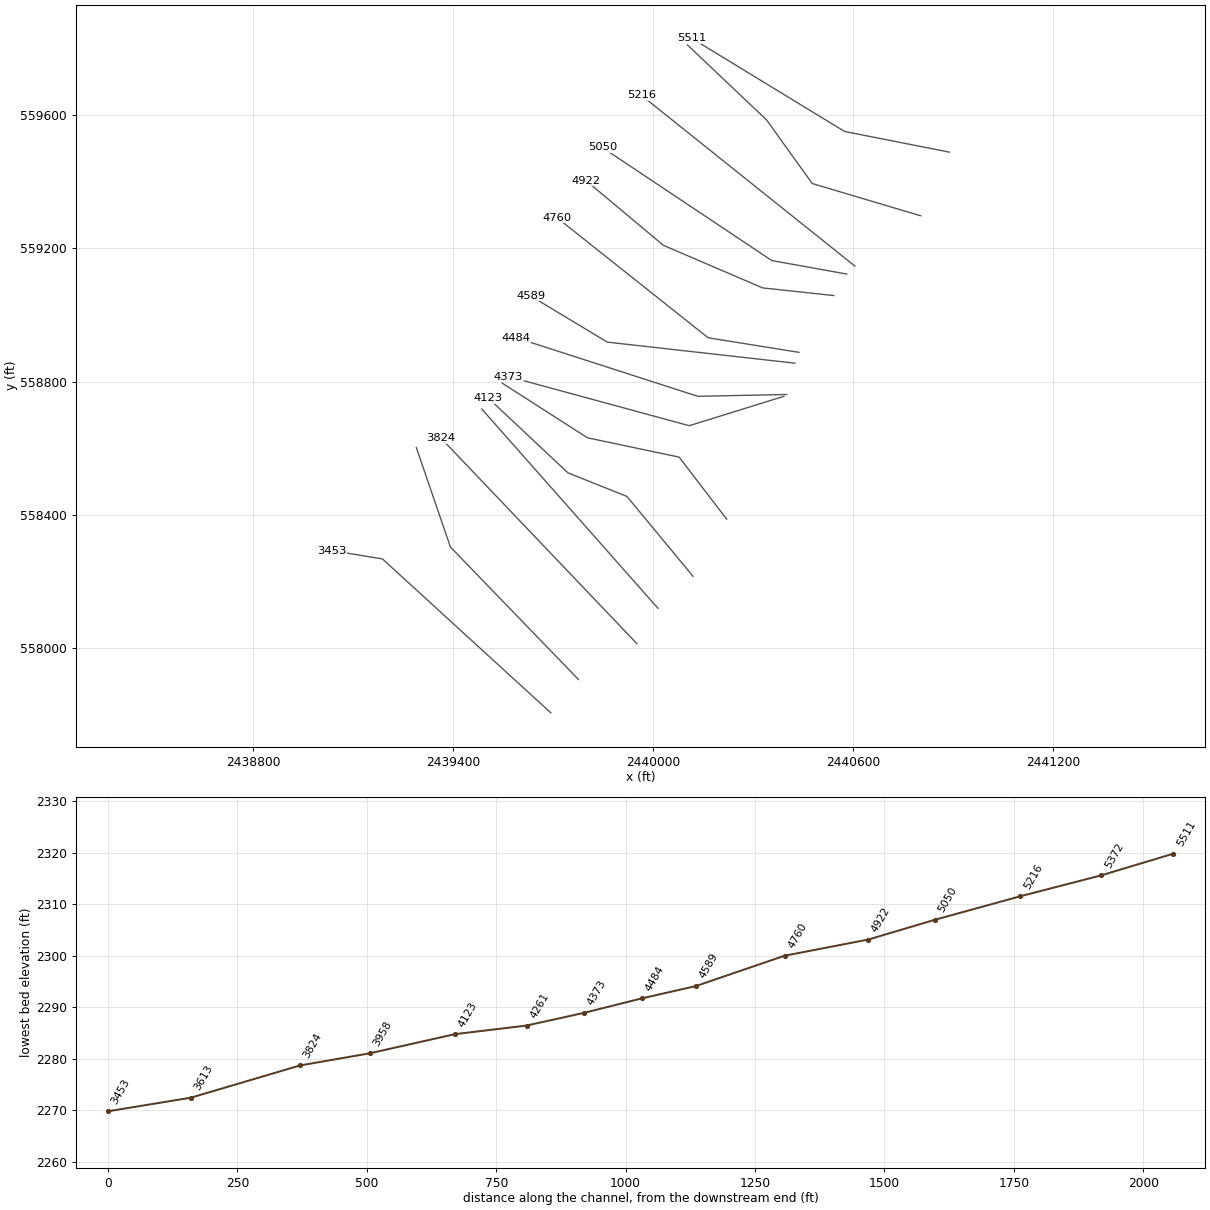
HEC-RAS study STAUFLERN.prj: STAUFLERN

--- STAUFLERN.g01 (geometry) --- (continued)

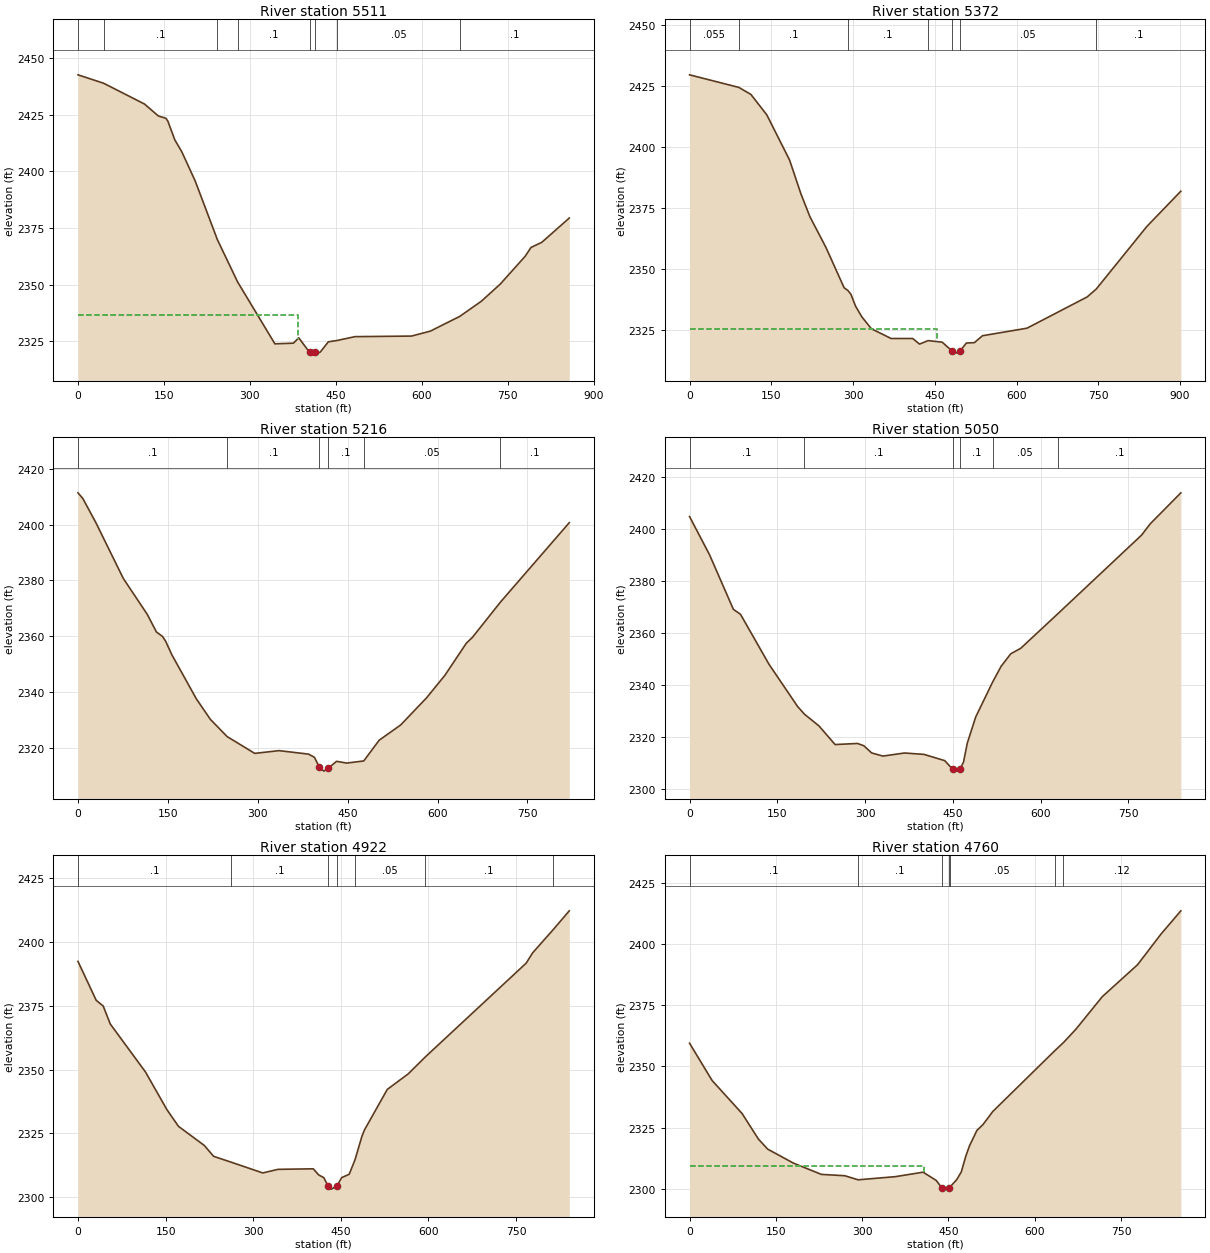
Type RM Length L Ch R = 1 ,5511    ,142.5,139.3,134.9
XS GIS Cut Line= 3
      2440888.31      559487.8892440573.84525599  559549.8555115
     2440115.486      559829.115
#Sta/Elev= 30
       0 2442.55   44.582438.857     116 2429.68   140.4 2424.38   153.5 2423.37
   156.9 2422.07   168.9 2413.89   181.2 2408.58   204.6 2395.68  243.332369.787
  278.662351.136   343.6  2323.9   375.9 2324.19   385.2 2326.56     404 2320.18
   413.5 2320.11     418  2319.8   422.7 2320.26   436.8 2324.79  451.682325.356
   483.3 2327.07   581.9 2327.32   614.7 2329.49  666.132336.009   703.7 2342.67
   736.5 2350.18   780.2  2362.5   790.4  2366.4   809.3 2368.68   857.2 2379.39
#Mann= 8 ,-1 , 0
       0    .055       0   44.58      .1       0  243.33     .12       0
  278.66      .1       0     404    .045       0   413.5      .1       0
  451.68     .05       0  666.13      .1       0
#XS Ineff= 2 , 0
          383.87 2336.82
Permanent Ineff=
       F       F
Bank Sta=404,413.5
XS Rating Curve= 0 ,0
Exp/Cntr=0.3,0.1

Type RM Length L Ch R = 1 ,5372    ,153.2,156.2,159.7
XS GIS Cut Line= 4
2440802.43053529559297.0134886582440476.87102968559393.796214744
2440339.92195337559584.4122559862440102.45513957  559809.2446977
#Sta/Elev= 30
       0 2429.66   90.392424.507   112.5 2421.64   141.7 2413.27   183.5 2394.75
   204.3 2380.91     221 2371.43   250.2 2358.94   283.6 2342.39  290.67 2341.22
   296.1 2339.71   304.5 2334.88   316.2 2330.43   333.7 2325.57   369.9 2321.58
   409.3 2321.59     422  2319.3  437.652320.718   463.5 2320.09   481.52316.499
   488.1 2315.59   496.5 2316.51   507.9 2319.72   522.6 2319.89   537.4 2322.72
   619.1 2325.81   729.5 2338.62   746.22341.863     839 2367.51   901.4 2381.97
#Mann= 7 ,-1 , 0
       0    .055       0   90.39      .1       0  290.67      .1       0
  437.65     .05       0   481.5    .045       0   496.5     .05       0
   746.2      .1       0
#XS Ineff= 2 , 0
          453.83 2325.45
Permanent Ineff=
       F       F
Bank Sta=481.5,496.5
XS Rating Curve= 0 ,0
Exp/Cntr=0.3,0.1

Type RM Length L Ch R = 1 ,5216    ,164.8,165.5,166.4
XS GIS Cut Line= 2
      2440604.88      559146.258     2439964.465      559658.003
#Sta/Elev= 30
       0 2411.38     8.1 2409.35    30.2 2400.54    75.7 2380.64   115.6 2367.78
   130.9 2361.46   141.2 2359.82   146.3 2358.14   156.5 2353.34   197.5 2337.47
   220.9 2330.11  248.812323.938   294.9  2317.9   335.7 2318.88   384.7 2317.63
   394.5  2316.5   402.92312.921   410.3 2311.53   417.92312.637   431.5 2315.05
   448.4 2314.42  476.85 2315.18   502.6 2322.62   538.5  2328.1   581.5 2337.79
   612.2 2345.89     648 2357.42   658.3 2359.55  704.882372.163   819.8 2400.67
#Mann= 6 ,-1 , 0
       0      .1       0  248.81      .1       0   402.9    .045       0
   417.9      .1       0  476.85     .05       0  704.88      .1       0
Bank Sta=402.9,417.9
XS Rating Curve= 0 ,0
Exp/Cntr=0.3,0.1

Type RM Length L Ch R = 1 ,5050    ,126.6,128.3,130.5
XS GIS Cut Line= 3
2440580.25293037559122.4170699432440355.36591311559162.936493258
2439847.02930214559501.860953214
#Sta/Elev= 30
       0 2404.75    34.2 2390.06    74.9  2369.1      87 2367.22   135.8 2347.99
   184.6 2331.79  196.272328.844   221.2 2324.31   248.7 2317.16   287.1 2317.58
   297.9 2316.68   311.1 2313.95   330.4 2312.73   367.1 2313.91   400.6 2313.38
   436.1 2310.98   449.5 2307.67   455.4 2306.95   462.12307.773   468.1 2310.39
   474.6 2317.72     489 2327.76  517.712341.096   532.3 2347.18   548.8 2352.02
   565.9 2354.14  629.61 2367.48   772.6 2397.67     787 2401.92   839.5 2413.87
#Mann= 6 ,-1 , 0
       0      .1       0  196.27      .1       0   449.5    .045       0
   462.1      .1       0  517.71     .05       0  629.61      .1       0
Bank Sta=449.5,462.1
XS Rating Curve= 0 ,0
Exp/Cntr=0.3,0.1

Type RM Length L Ch R = 1 ,4922    ,165.2,162,158.8
XS GIS Cut Line= 4
2440541.58716289559057.9282326722440328.02726188559080.920539572
2440030.33972628559208.5009119722439798.18623267559402.508860586
#Sta/Elev= 30
       0 2392.46    31.2  2377.2    43.2 2374.95    55.3 2367.91   115.7 2349.04
   152.1 2334.37     172 2327.77   216.3 2320.25   232.3 2315.98  262.272313.691
   316.4 2309.47   342.5 2310.88   402.8 2311.09   412.2 2308.69   420.9 2307.62
   428.12304.387   433.9 2303.12   443.1  2304.3   451.6 2307.65   464.4 2308.95
  474.352314.649   486.1 2323.79   490.5 2326.33   529.6 2342.24   565.4 2348.33
  594.762354.991   767.6 2391.82   778.3 2395.77  812.532404.623   841.2  2412.3
#Mann= 7 ,-1 , 0
       0      .1       0  262.27      .1       0   428.1    .045       0
   443.1      .1       0  474.35     .05       0  594.76      .1       0
  812.53     .12       0
Bank Sta=428.1,443.1
XS Rating Curve= 0 ,0
Exp/Cntr=0.3,0.1

Type RM Length L Ch R = 1 ,4760    ,164.4,171.2,176.3
XS GIS Cut Line= 3
     2440436.817      558887.7342440164.55955844558931.414767171
2439711.76304647559290.761790643
#Sta/Elev= 30
       0 2359.47    39.2 2344.27    91.4 2330.77   119.7 2320.37   135.9 2316.26
   180.5 2310.58   229.1 2305.98   269.6 2305.44  293.052303.768   357.8 2305.06
   405.9 2306.88   428.6 2303.53   438.7 2300.44   446.7 2299.97   450.1 2300.31
     4522300.707   464.3 2303.84   472.2 2306.96   480.1 2313.43   486.5 2317.62
   499.4 2323.93   509.9 2326.28   526.9 2331.61  634.472356.363  649.412359.642
   671.4 2365.17   717.3 2378.46   778.6 2391.49   819.4 2404.01   853.8 2413.46
#Mann= 7 ,-1 , 0
       0      .1       0  293.05      .1       0   438.7    .045       0
   450.1      .1       0     452     .05       0  634.47      .1       0
  649.41     .12       0
#XS Ineff= 2 , 0
          406.82  2309.5
Permanent Ineff=
       F       F
Bank Sta=438.7,450.1
XS Rating Curve= 0 ,0
Exp/Cntr=0.3,0.1

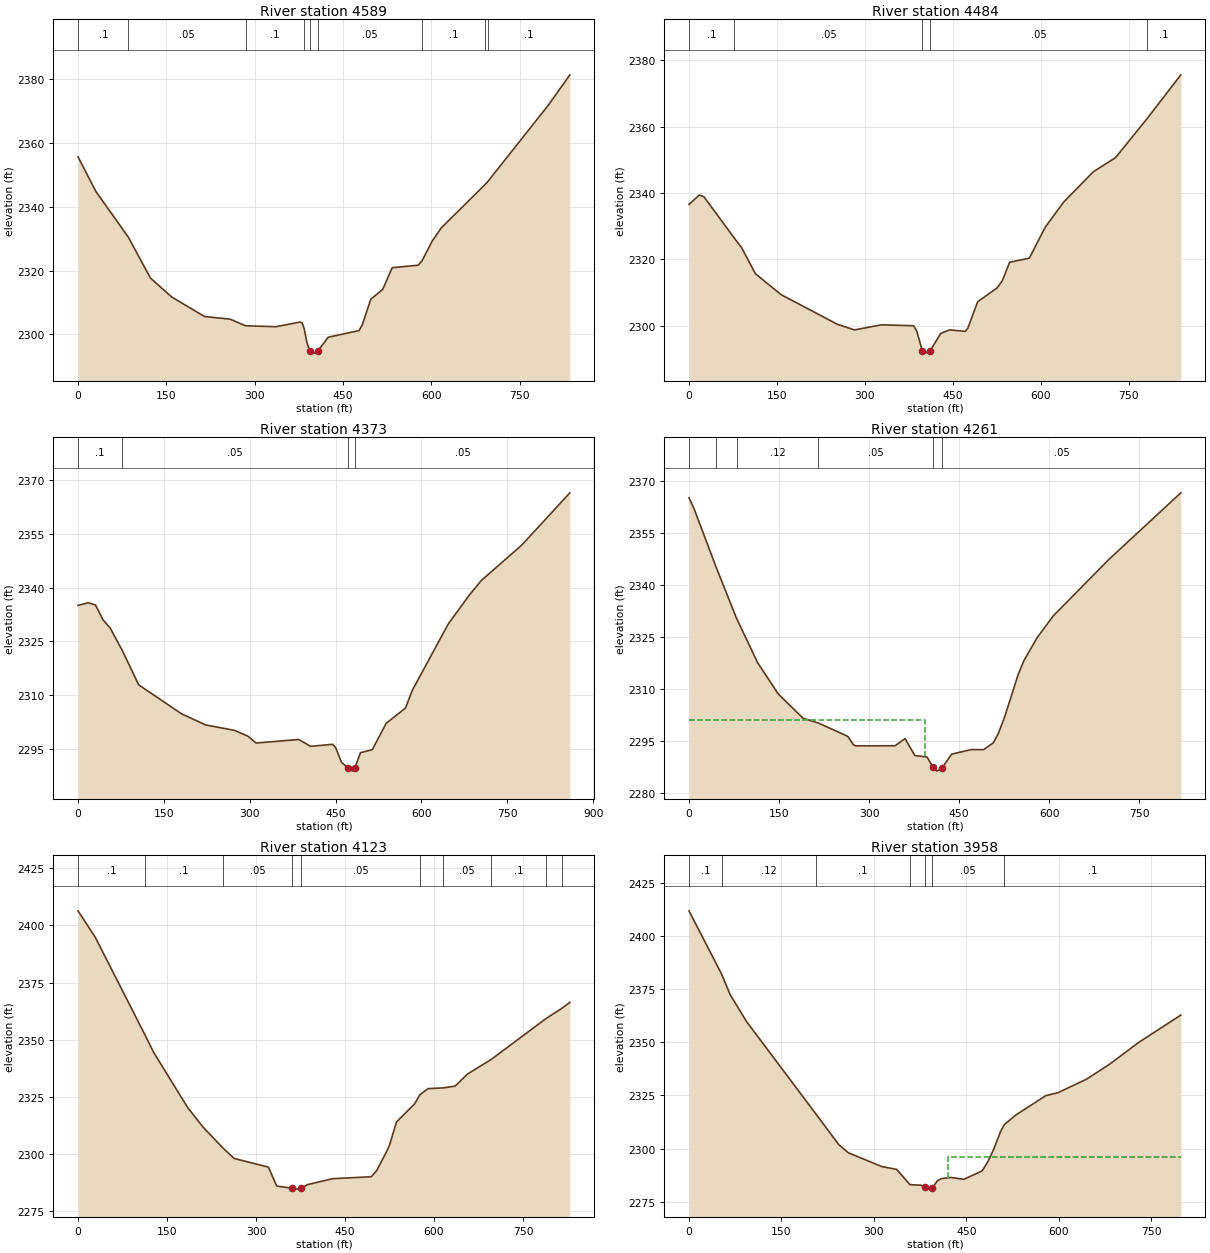
Type RM Length L Ch R = 1 ,4589    ,107.1,104.9,102.5
XS GIS Cut Line= 3
     2440424.886      558855.2462439861.75137703558918.407446156
2439631.66686059559057.096163043
#Sta/Elev= 30
       0 2355.71    30.3 2344.85   85.742330.412     123 2317.65   159.3 2311.68
   214.9 2305.58   258.3 2304.75  284.622302.664   336.3 2302.38   376.6 2303.82
   380.6 2303.64  384.052301.772   388.8 2297.43   393.3  2294.8   400.7 2294.08
   406.9 2294.66   424.9 2299.06   477.2 2301.16   482.7 2302.92   497.3 2311.02
   517.5 2314.09   533.6  2320.9   577.7 2321.68  584.172323.031     601 2329.09
     617 2333.41  691.192346.973  695.772347.897     799 2371.97   835.3 2381.44
#Mann= 9 ,-1 , 0
       0      .1       0   85.74     .05       0  284.62      .1       0
  384.05     .05       0   393.3    .045       0   406.9     .05       0
  584.17      .1       0  691.19     .05       0  695.77      .1       0
Bank Sta=393.3,406.9
XS Rating Curve= 0 ,0
Exp/Cntr=0.3,0.1

Type RM Length L Ch R = 1 ,4484    ,108.2,111,109.1
XS GIS Cut Line= 3
2440400.07230246558761.4044888152440133.61907536558755.894352742
2439588.76513957  558931.4693954
#Sta/Elev= 30
       0 2336.52    17.5 2339.36    25.5 2338.86   77.442326.348    89.5 2323.57
   113.5  2315.6   157.2 2309.31   253.5 2300.35   282.3 2298.68   328.5 2300.22
   383.1 2299.94   388.5 2298.36   398.1 2292.38   401.2 2291.68   410.8 2292.19
   429.3 2297.59   444.4 2298.69   471.4 2298.24   475.6 2299.16   492.4 2307.17
     526  2311.4   534.4 2313.48     547 2319.09   580.6 2320.33   607.8 2329.69
   639.4  2337.3   689.9  2346.4   727.7 2350.66  781.622362.449     839 2375.62
#Mann= 5 ,-1 , 0
       0      .1       0   77.44     .05       0   398.1    .045       0
   410.8     .05       0  781.62      .1       0
Bank Sta=398.1,410.8
XS Rating Curve= 0 ,0
Exp/Cntr=0.3,0.1

Type RM Length L Ch R = 1 ,4373    ,110.5,111.3,111.8
XS GIS Cut Line= 3
2440391.81744808558755.8943527422440107.79923809558667.803143227
2439565.58265539 558815.12809707
#Sta/Elev= 30
       0 2335.03      18 2335.78    30.6 2335.14    43.7 2331.02    56.4 2328.69
   76.95 2322.61     106 2312.91   181.3  2304.8   223.2 2301.74   273.5 2300.23
   297.4 2298.55     311 2296.71   385.6 2297.69   406.3 2295.79   444.9 2296.35
   450.4 2295.32   460.2 2291.34   471.42289.818   479.7 2288.88   483.82289.798
   493.4 2294.01   514.1 2294.86   538.4 2302.21   572.1 2306.45     584 2311.38
   646.7 2329.84     684    2338   704.7 2342.01   775.2 2351.83   859.2 2366.39
#Mann= 4 ,-1 , 0
       0      .1       0   76.95     .05       0   471.4    .045       0
   483.8     .05       0
Bank Sta=471.4,483.8
XS Rating Curve= 0 ,0
Exp/Cntr(USF)=0,0
Exp/Cntr=0.3,0.1

Type RM Length L Ch R = 1 ,4261    ,140.1,138.3,135.8
XS GIS Cut Line= 4
2440220.16893006558387.6926509142440077.42295895558573.636677884
  2439802.540023558631.5204650282439546.57983727558795.470441871
#Sta/Elev= 30
       0 2365.14     8.6 2361.94   44.412345.523   79.272330.419   114.5  2317.6
   148.6 2308.67   190.1 2301.63  215.692300.256   264.5 2296.42   274.1 2293.98
     278 2293.69   343.5 2293.72   359.9 2295.77   376.2 2290.91   396.7 2290.46
   406.52287.521     413 2286.41   421.2  2287.2   437.5  2291.3   470.2 2292.62
   490.7 2292.59     507 2294.58   515.2 2297.21   526.1 2302.14   548.4 2314.26
   557.9 2318.22   580.1  2324.9   607.1 2331.17   698.8 2347.28   819.3 2366.57
#Mann= 6 ,-1 , 0
       0     .12       0   44.41      .1       0   79.27     .12       0
  215.69     .05       0   406.5    .045       0   421.2     .05       0
#XS Ineff= 2 , 0
       0   392.6    2301               0
Permanent Ineff=
       F       F
Bank Sta=406.5,421.2
XS Rating Curve= 0 ,0
Exp/Cntr=0.3,0.1

Type RM Length L Ch R = 1 ,4123    ,168.1,164.6,155.6
XS GIS Cut Line= 4
2440119.20284753558216.3004942992439920.94666666558455.758990991
2439744.05393965558526.356861499     2439505.036      558750.393
#Sta/Elev= 30
       0 2406.32    28.9 2394.86  112.65 2352.24   127.5 2344.49   184.6 2320.47
   210.6 2311.88  244.582302.628   263.3 2298.13   320.9 2294.36   334.9 2286.09
   361.4 2285.11   369.3 2284.74   376.3 2285.11   386.6  2286.7   429.6 2289.32
   494.2 2290.15   503.2 2292.78   519.7 2300.95   525.2 2304.11   536.6 2314.02
   567.5 2322.06  576.232326.002   590.1 2328.65   615.32328.961   635.4 2329.73
   656.7 2335.08  695.942341.313  788.292359.178  815.652363.772   828.9 2366.31
#Mann= 10 ,-1 , 0
       0      .1       0  112.65      .1       0  244.58     .05       0
   361.4    .045       0   376.3     .05       0  576.23      .1       0
   615.3     .05       0  695.94      .1       0  788.29     .05       0
  815.65      .1       0
Bank Sta=361.4,376.3
XS Rating Curve= 0 ,0
Exp/Cntr=0.3,0.1

Type RM Length L Ch R = 1 ,3958    ,134.4,134.7,135
XS GIS Cut Line= 2
 2440013.9178839558120.521535129      2439485.22       558717.96
#Sta/Elev= 30
       0 2411.74   52.872382.055    66.8 2372.38    93.5 2359.68  205.662316.414
     243 2301.92   258.4 2298.12   312.7 2291.62   336.9 2290.29  358.462283.127
   376.5 2282.84   383.4 2281.81   391.2 2281.02   394.8 2281.72   403.3 2285.03
   409.3 2285.95   424.6 2286.51     446 2285.63   475.7 2289.63   485.4 2294.23
   493.8 2299.44   505.3 2307.97  511.26 2311.27     530 2315.82   578.9 2324.93
   598.8 2326.35   644.7 2332.64   681.7 2339.58     729 2349.84   797.8 2362.78
#Mann= 7 ,-1 , 0
       0      .1       0   52.87     .12       0  205.66      .1       0
  358.46     .05       0   383.4    .045       0   394.8     .05       0
  511.26      .1       0
#XS Ineff= 2 , 0
                          419.98         2295.97
Permanent Ineff=
       F       F
Bank Sta=383.4,394.8
XS Rating Curve= 0 ,0
Exp/Cntr=0.3,0.1

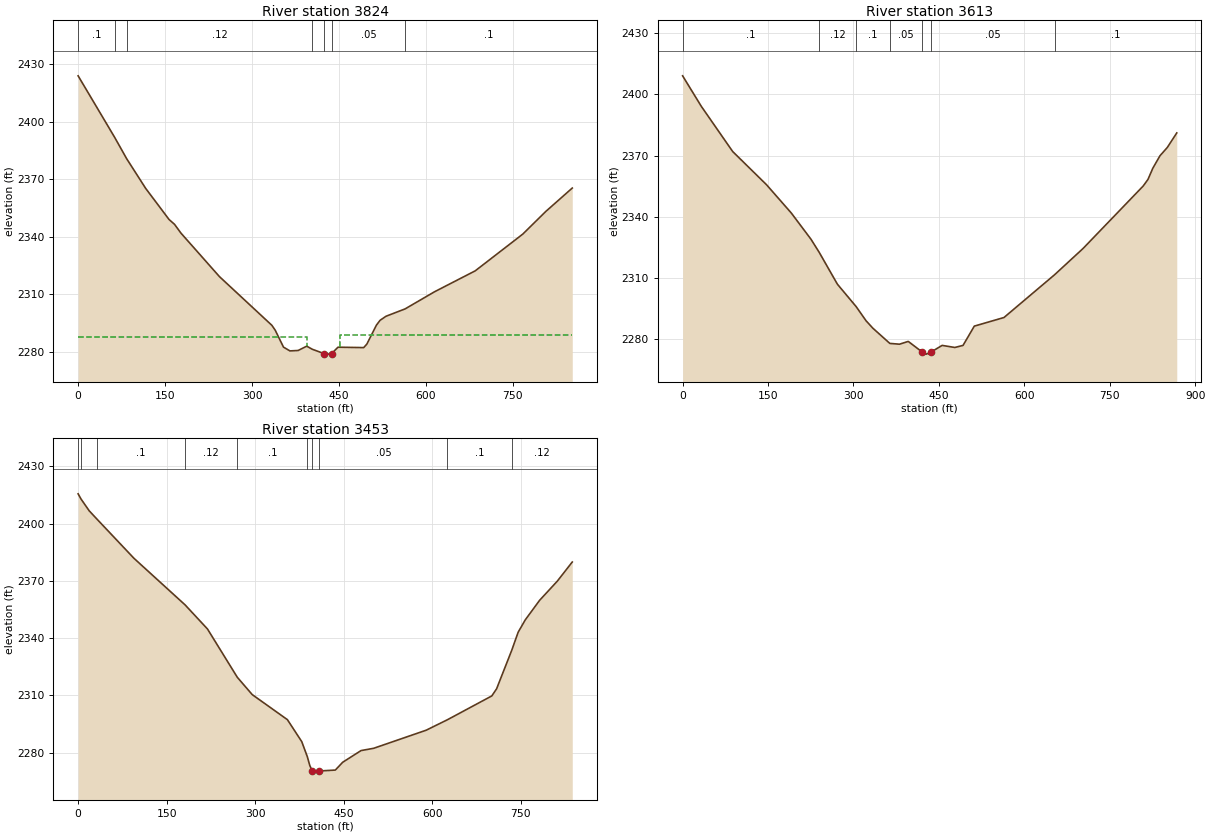
Type RM Length L Ch R = 1 ,3824    ,210.5,210.8,211.7
XS GIS Cut Line= 2
2439950.98523267558014.1667674862439362.45546503558630.931418557
#Sta/Elev= 30
       0 2423.91   63.252391.691    83.72380.676   116.6 2365.14   156.9 2348.92
   166.4 2346.38   177.4 2341.82   243.8 2319.12   334.3 2293.68     340 2291.17
   354.3 2282.32   365.4 2280.34   379.6 2280.57   394.4 2282.81  404.022281.193
     425 2278.87   431.7 2278.66   437.3 2278.92   448.3 2282.27   492.7 2282.07
   498.1 2283.89   514.7 2293.83     521 2296.33   531.2 2298.43  564.192302.275
   614.6 2311.16   685.1 2322.13   767.1 2341.29   806.7 2353.09   852.5 2365.34
#Mann= 7 ,-1 , 0
       0      .1       0   63.25      .1       0    83.7     .12       0
  404.02     .05       0     425    .045       0   437.3     .05       0
  564.19      .1       0
#XS Ineff= 2 , 0
          394.53 2287.44  452.22         2288.56
Permanent Ineff=
       F       F
Bank Sta=425,437.3
XS Rating Curve= 0 ,0
Exp/Cntr=0.3,0.1

Type RM Length L Ch R = 1 ,3613    ,158.9,160.1,161.2
XS GIS Cut Line= 3
2439775.42516273557906.9780464712439391.25776701558304.160721014
2439288.98374401558602.231418557
#Sta/Elev= 30
       0 2409.15    32.8 2394.17    87.9 2371.96   147.3 2355.65   190.9 2341.72
   225.5 2328.82   239.92322.396   271.8 2306.77  304.59 2295.79   322.2 2288.77
     334 2285.16  363.852277.665   380.8 2277.28   396.2 2278.65   419.82273.629
   427.9  2272.4   435.8 2273.34   455.7 2276.69     478 2275.67   492.4 2276.69
   512.2 2286.16   564.3 2290.39  653.062311.381   703.1 2324.29   808.8 2355.02
   817.2 2358.27   825.7 2363.77   838.2 2369.87   851.1 2373.95   867.7 2381.09
#Mann= 7 ,-1 , 0
       0      .1       0   239.9     .12       0  304.59      .1       0
  363.85     .05       0   419.8    .045       0   435.8     .05       0
  653.06      .1       0
Bank Sta=419.8,435.8
XS Rating Curve= 0 ,0
Exp/Cntr=0.3,0.1

Type RM Length L Ch R = 1 ,3453    ,195.5,195.9,196.6
XS GIS Cut Line= 3
 2439692.5236977  557807.05439542439187.39798006558268.355072497
2439036.22165107558293.382767328
#Sta/Elev= 30
       0 2415.64    4.922412.922    18.8 2406.73   32.362402.237    94.6 2381.85
  181.272357.421   219.2 2344.79  269.732319.477     295  2310.4   354.6 2297.27
   378.9 2285.76  388.412277.827   392.5 2273.27   396.7  2270.4   400.1 2269.76
   408.7 2270.35   435.8 2270.84   448.3 2274.93   479.4 2281.06   500.8 2282.25
   589.8 2291.74  625.78 2297.22     701 2309.71   709.1 2313.45  734.612333.521
   745.7 2343.15   757.7 2349.59     782 2359.83   811.8 2369.81   837.3  2379.9
#Mann= 10 ,-1 , 0
       0      .1       0    4.92      .1       0   32.36      .1       0
  181.27     .12       0  269.73      .1       0  388.41     .05       0
   396.7    .045       0   408.7     .05       0  625.78      .1       0
  734.61     .12       0
Bank Sta=396.7,408.7
XS Rating Curve= 0 ,0
Exp/Cntr=0.3,0.1