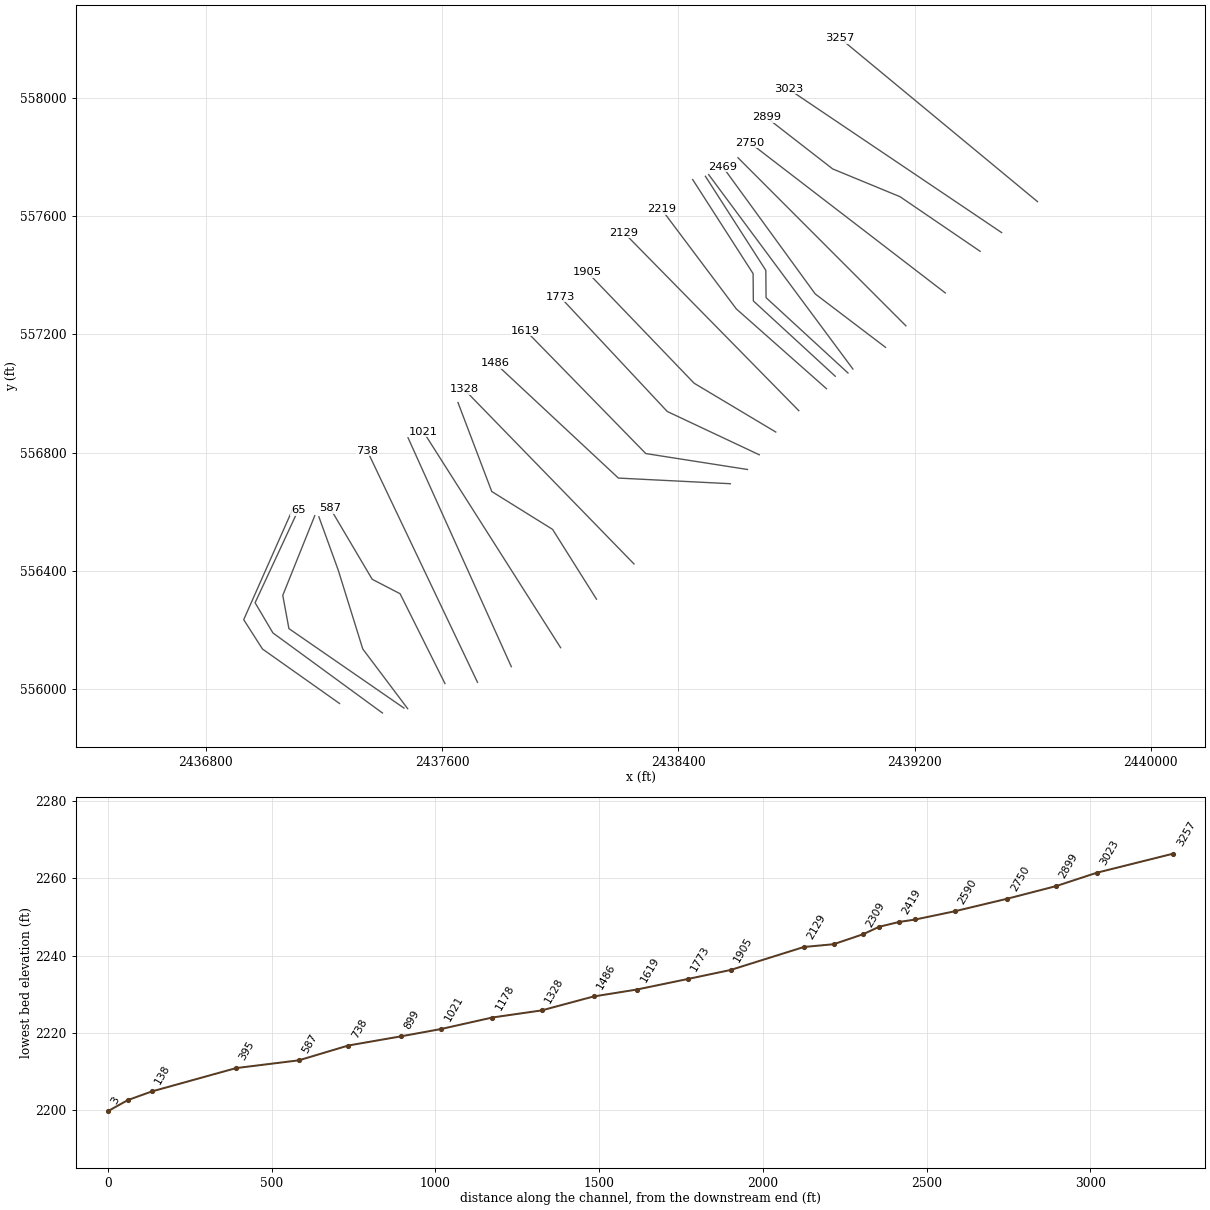
HEC-RAS study STAUFLERN.prj: STAUFLERN

--- STAUFLERN.g01 (geometry) --- (continued)

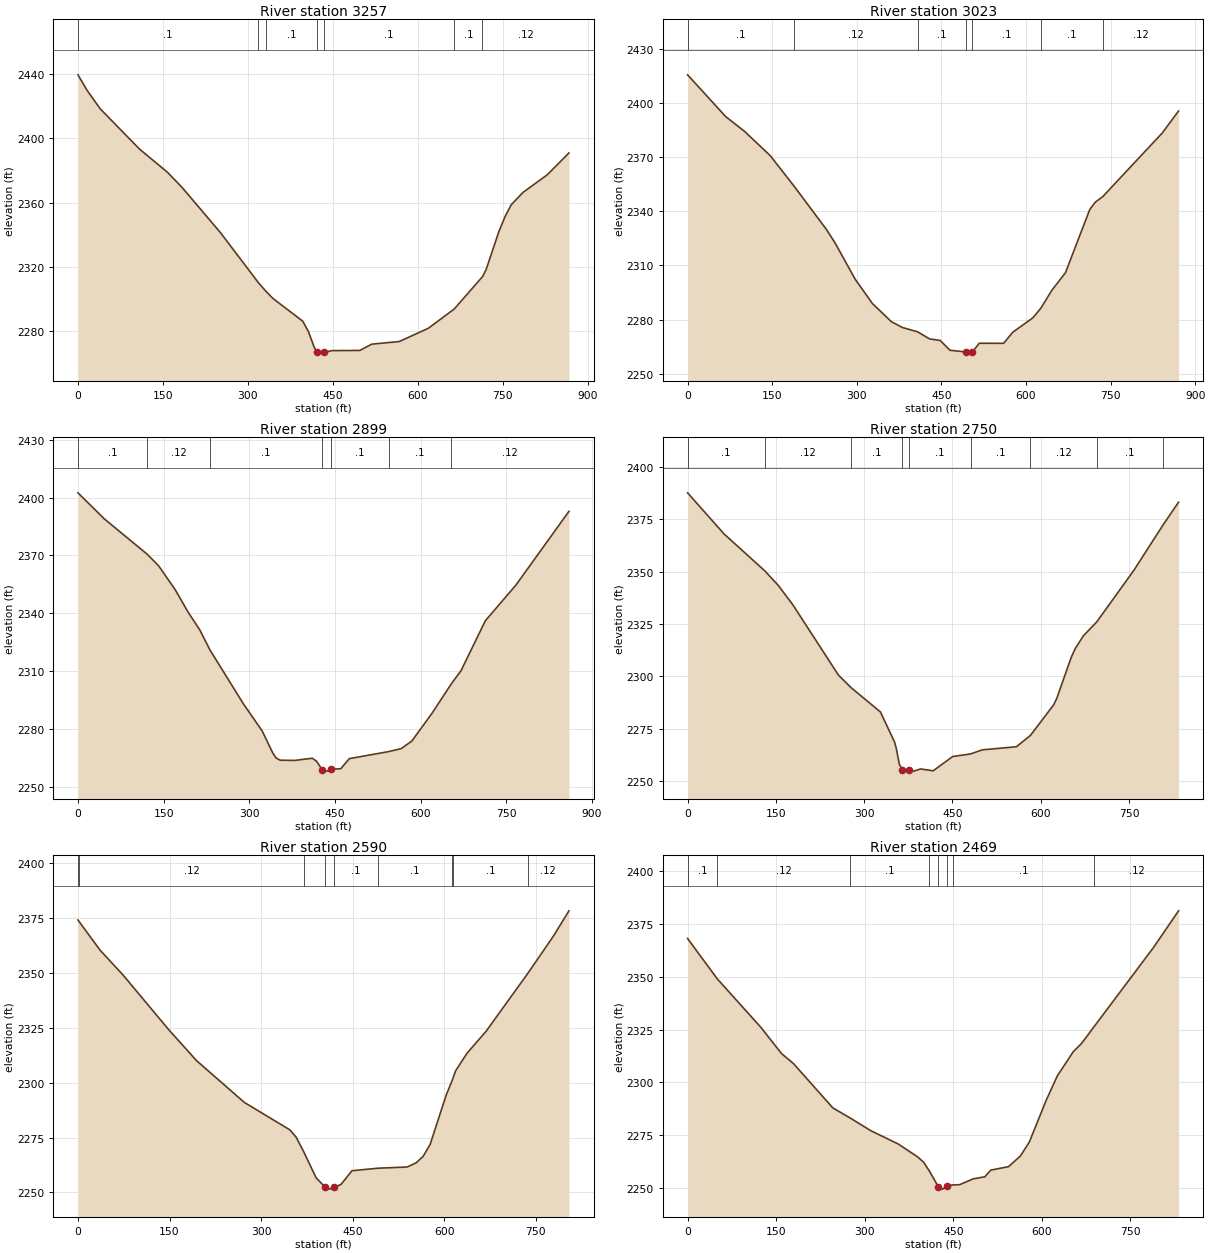
Type RM Length L Ch R = 1 ,3257    ,233.2,233.8,235.1
XS GIS Cut Line= 2
2439616.19911626557649.4186975432438948.13183711558201.923023157
#Sta/Elev= 30
       0  2439.5    16.1 2429.86    39.5 2418.29   108.5 2393.39   158.2 2378.84
   183.7 2369.54   251.9 2341.23  318.69  2310.2  332.772304.548   344.5 2300.37
   396.8 2286.33   406.8 2279.92   417.2 2270.04   422.3 2266.92     428 2266.44
   434.9 2266.85   448.3    2268   497.6 2268.12   518.9 2272.03   567.2 2273.64
   618.4 2281.85  664.072293.782  714.132313.938   720.6 2318.33   743.3 2342.14
   754.5 2351.64   764.9 2358.65   785.7 2366.35   828.6 2377.33   866.9 2390.93
#Mann= 7 ,-1 , 0
       0      .1       0  318.69     .12       0  332.77      .1       0
   422.3    .045       0   434.9      .1       0  664.07      .1       0
  714.13     .12       0
Bank Sta=422.3,434.9
XS Rating Curve= 0 ,0
Exp/Cntr=0.3,0.1

Type RM Length L Ch R = 1 ,3023    ,121.7,124,125.2
XS GIS Cut Line= 2
2439494.70467072557544.7246004692438772.42425554558030.745066756
#Sta/Elev= 30
       0 2415.46    67.6 2392.36   101.2 2384.13   146.6 2370.73  189.092353.762
   245.9 2330.04   261.3 2322.57   297.1 2302.41   327.8 2288.91   361.5 2278.85
   380.8 2275.68  407.782273.268   429.1 2269.37     448 2268.47   465.3 2263.07
     4932262.139   499.9 2261.48   504.9 2262.09   517.2 2266.95   560.4  2266.9
   576.5 2273.02   612.1 2280.98  626.462286.349     646 2296.29   670.1    2306
   713.1  2340.9   723.1 2345.08  735.812347.957   841.6 2383.24   870.6 2395.44
#Mann= 7 ,-1 , 0
       0      .1       0  189.09     .12       0  407.78      .1       0
     493    .045       0   504.9      .1       0  626.46      .1       0
  735.81     .12       0
Bank Sta=493,504.9
XS Rating Curve= 0 ,0
Exp/Cntr(USF)=0,0
Exp/Cntr=0.3,0.1

Type RM Length L Ch R = 1 ,2899    ,150.9,149,145.9
XS GIS Cut Line= 4
2439421.96114468557481.3721497932439150.44017377557666.229717041
2438922.64488598557760.0482893652438697.49385276557934.855994889
#Sta/Elev= 30
       0 2402.43    46.4 2388.85  121.512370.513   141.4 2364.52   170.2  2352.2
   192.6 2340.67   213.4 2331.29  231.13 2320.93   289.4  2293.1   322.8 2278.79
   341.1 2267.48   346.9 2264.87   354.1 2263.68   380.1 2263.59   410.3 2264.71
   417.4  2263.3   427.92258.766   436.3 2258.02   442.82258.924   460.3 2259.29
   475.2 2264.49   543.92268.143   566.1  2269.7   584.8 2273.64   620.3 2288.13
  653.662303.217   670.9 2310.15   713.4 2336.01   767.1  2354.6   859.9 2392.83
#Mann= 7 ,-1 , 0
       0      .1       0  121.51     .12       0  231.13      .1       0
   427.9    .045       0   442.8      .1       0   543.9      .1       0
  653.66     .12       0
Bank Sta=427.9,442.8
XS Rating Curve= 0 ,0
Exp/Cntr=0.3,0.1

Type RM Length L Ch R = 1 ,2750    ,159.7,160.1,158.1
XS GIS Cut Line= 2
2439304.00914054557340.5285017852438642.48128365557848.487391898
#Sta/Elev= 30
       0 2387.65    62.1 2367.98  131.222350.384   154.5  2343.3   179.3 2333.99
   256.3  2300.6  277.562294.658   327.6 2283.01   351.5 2268.73   354.6 2265.56
   359.7 2258.07   364.7  2255.5   375.7 2255.49   384.3 2254.75     396  2255.8
   417.2  2254.9   450.4 2261.72  480.712262.961   500.8 2264.92   558.6 2266.39
  582.45  2271.8   621.9  2286.4   627.1 2289.43   652.1 2309.34   658.5 2313.22
   672.3 2319.34  695.262326.053   758.7 2350.87  808.072372.461   834.1 2383.19
#Mann= 9 ,-1 , 0
       0      .1       0  131.22     .12       0  277.56      .1       0
   364.7    .045       0   375.7      .1       0  480.71      .1       0
  582.45     .12       0  695.26      .1       0  808.07     .12       0
Bank Sta=364.7,375.7
XS Rating Curve= 0 ,0
Exp/Cntr(USF)=0,0
Exp/Cntr=0.3,0.1

Type RM Length L Ch R = 1 ,2590    ,122.8,121,118.9
XS GIS Cut Line= 2
2439170.69102653557229.1488115942438601.97957813557797.860259994
#Sta/Elev= 30
       0 2374.04    2.16 2373.21      36 2360.37    74.6 2348.74   149.2 2323.92
   194.4 2309.96   272.5 2290.98   347.1 2278.49   357.4 2275.15  369.472268.716
   390.2 2256.61   405.4  2252.3   411.1  2251.5   419.6 2252.26   430.9 2253.65
   448.9 2259.88  491.912261.031   539.4 2261.57   554.3 2263.53   565.6 2266.49
   576.9 2271.84   603.4 2294.48  612.172300.382  614.352302.069   618.6 2305.33
   637.4 2313.41   668.5 2323.33  736.78 2349.66   778.8 2366.66   804.3  2378.2
#Mann= 9 ,-1 , 0
       0      .1       0    2.16     .12       0  369.47      .1       0
   405.4    .045       0   419.6      .1       0  491.91      .1       0
  612.17     .12       0  614.35      .1       0  736.78     .12       0
Bank Sta=405.4,419.6
XS Rating Curve= 0 ,0
Exp/Cntr(USF)=0,0
Exp/Cntr=0.3,0.1

Type RM Length L Ch R = 1 ,2469    ,50.2,50.4,50.5
XS GIS Cut Line= 3
2439101.50061292557156.5832558642438863.55309297557337.153359658
2438549.95614724 557767.93629192
#Sta/Elev= 30
       0 2368.16   50.262349.026     124 2326.07   159.1 2313.61   179.2  2308.9
   246.1 2287.83   275.22283.093   310.4 2277.03   356.4 2270.79   389.6 2264.64
   399.5 2262.17  409.292258.038   424.52250.531     432 2249.35   439.52250.861
  449.242251.349   460.6 2251.44   483.6 2254.22   503.4 2255.19   513.3 2258.34
   543.7 2260.02   563.7 2265.08   578.7 2271.63   607.2 2291.38   626.2 2303.03
   653.4 2314.58   666.8 2318.26  688.922326.535   789.3 2363.98   831.5 2381.26
#Mann= 8 ,-1 , 0
       0      .1       0   50.26     .12       0   275.2      .1       0
  409.29      .1       0   424.5    .045       0   439.5      .1       0
  449.24      .1       0  688.92     .12       0
Bank Sta=424.5,439.5
XS Rating Curve= 0 ,0
Exp/Cntr(USF)=0,0
Exp/Cntr=0.3,0.1

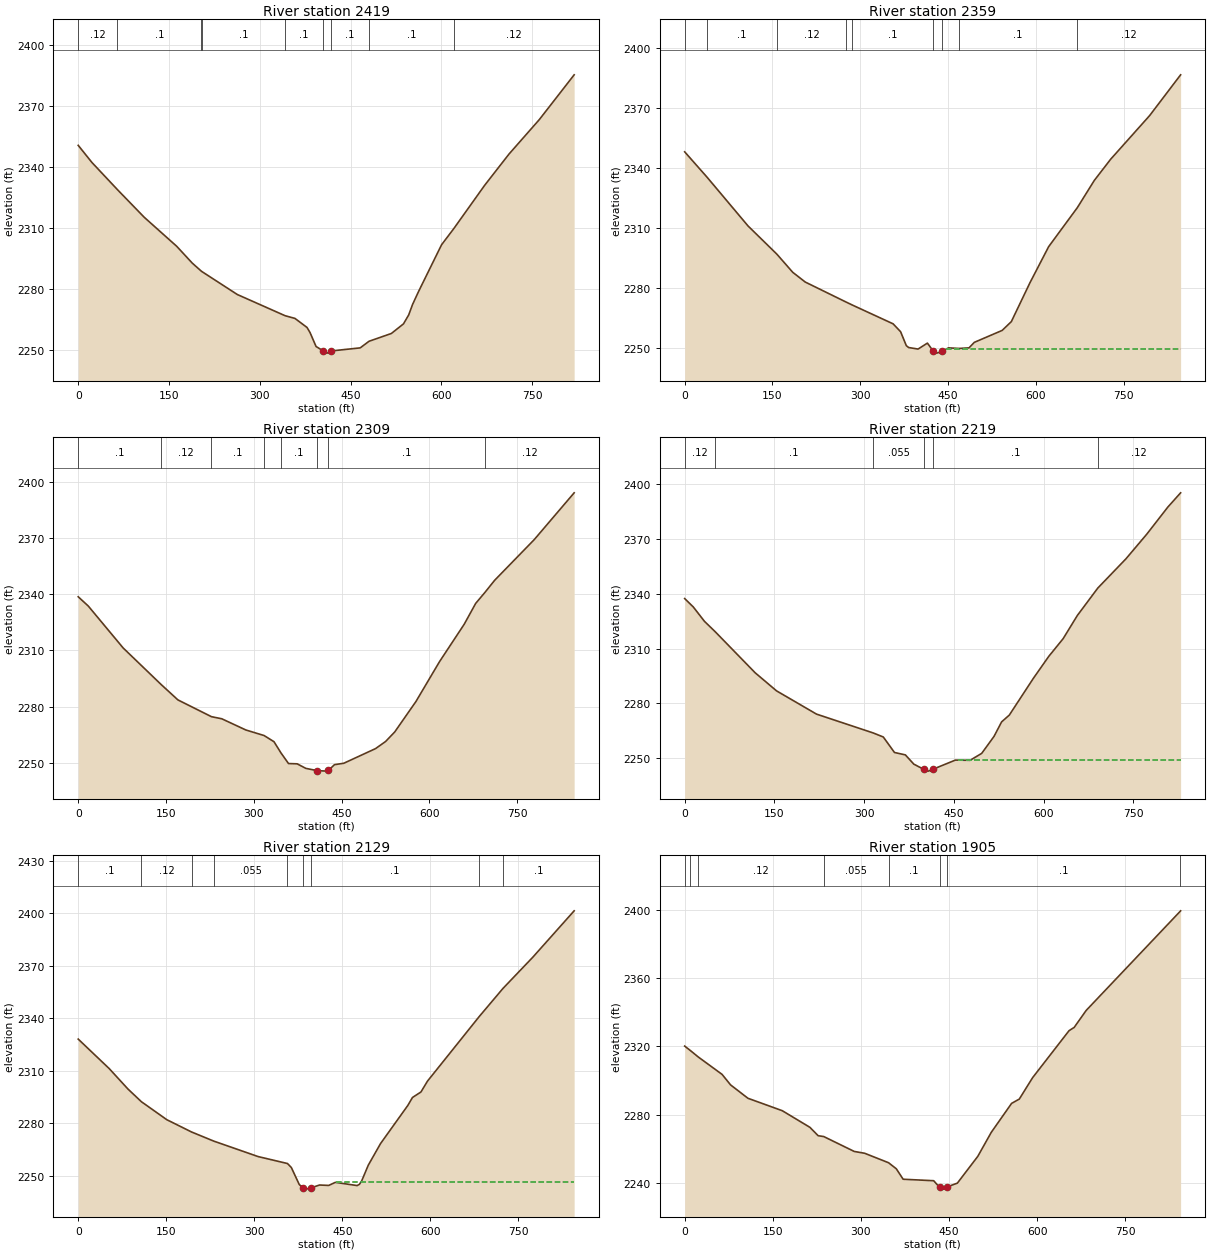
Type RM Length L Ch R = 1 ,2419    ,67.4,59.9,51.5
XS GIS Cut Line= 2
2438991.05515746557083.1951549052438502.70415746557740.935154905
#Sta/Elev= 30
       0 2350.59    22.7 2342.18   64.762328.884   108.9 2315.36   162.8 2301.06
   188.4 2292.84  203.292288.914  203.722288.809   262.8 2277.44  341.812267.039
     358 2265.73   377.9  2261.3   382.9 2258.82   392.9 2251.95   404.92249.767
   411.5  2248.7   417.8 2249.76   465.8 2251.28  480.342254.506   517.3 2258.34
   537.3 2263.05   545.9 2267.43   552.3 2272.57   562.2 2278.92   600.2 2301.84
  620.572309.835   671.4 2331.01   711.7 2346.35   761.5 2363.16   819.2 2385.17
#Mann= 9 ,-1 , 0
       0     .12       0   64.76      .1       0  203.29     .12       0
  203.72      .1       0  341.81      .1       0   404.9    .045       0
   417.8      .1       0  480.34      .1       0  620.57     .12       0
Bank Sta=404.9,417.8
XS Rating Curve= 0 ,0
Exp/Cntr=0.5,0.3

Type RM Length L Ch R = 1 ,2359    ,52.4,49.7,49
XS GIS Cut Line= 4
2438974.45141846557069.741786106 2438697.0923968557324.524684857
2438696.21408556557416.953221937     2438491.663      557735.145
#Sta/Elev= 30
       0 2348.07   38.542335.287   108.2 2311.04  157.452296.951   184.6 2287.87
     206 2282.99  276.362272.911  285.952271.569   356.1 2262.11   368.9 2258.17
   378.7 2251.18   382.7 2250.27   398.7  2249.5   414.7 2252.47   424.9 2248.39
   430.7 2247.47   440.4  2248.4   450.7 2250.11  468.582249.805   485.8  2250.1
   494.8 2252.85   542.4 2258.82   558.1 2263.22     590  2282.7   621.8 2300.65
   670.92320.193   699.9  2333.8   727.8 2344.37   794.4 2366.19   847.3 2386.55
#Mann= 9 ,-1 , 0
       0     .12       0   38.54      .1       0  157.45     .12       0
  276.36      .1       0  285.95      .1       0   424.9    .045       0
   440.4      .1       0  468.58      .1       0   670.9     .12       0
#XS Ineff= 2 , 0
          411.04  2249.6  446.98          2249.6
Permanent Ineff=
       F       F
Bank Sta=424.9,440.4
XS Rating Curve= 0 ,0
Exp/Cntr(USF)=0,0
Exp/Cntr=0.5,0.3

Type RM Length L Ch R = 1 ,2309    ,76.3,89.6,98.4
XS GIS Cut Line= 4
2438931.39304278557058.6696323582438654.03402112557313.452531109
2438653.15570987 557405.881068192438448.60462432557724.072846252
#Sta/Elev= 30
       0 2338.59    17.2 2333.64    76.8 2311.26  141.962291.672   170.3 2283.55
   227.62274.593   245.3 2273.46   286.3  2267.5  317.55 2264.52   334.5 2261.22
  346.512255.206   359.3 2249.57   374.1 2249.41   388.9 2246.99   408.12245.793
   424.6 2245.52   427.62245.914   437.8 2248.96   453.8 2249.73     508 2257.54
   525.2 2261.35   540.8 2266.44     577 2282.68   617.3 2303.96   659.4 2323.89
   679.1 2335.06  694.35 2340.71   711.5 2347.39     779 2369.06   847.3 2394.07
#Mann= 8 ,-1 , 0
       0      .1       0  141.96     .12       0   227.6      .1       0
  317.55      .1       0  346.51      .1       0   408.1    .045       0
   427.6      .1       0  694.35     .12       0
Bank Sta=408.1,427.6
XS Rating Curve= 0 ,0
Exp/Cntr=0.5,0.3

Type RM Length L Ch R = 1 ,2219    ,91.6,90.9,92.6
XS GIS Cut Line= 3
     2438901.524        557016.7     2438596.346      557286.517
     2438343.104      557623.682
#Sta/Elev= 30
       0 2337.38    14.4 2332.78    33.2 2324.87   50.752319.323   117.7  2296.8
   153.5 2286.88   220.3 2274.15  315.362263.807     332 2261.62   350.7 2253.14
   368.9 2251.83     383 2246.77   399.92243.878   407.4 2242.94   414.92243.957
   452.5 2248.98   477.1 2248.86   496.5 2252.66   517.1 2261.95   529.8  2269.9
   542.6 2273.59   582.8 2293.69   608.5  2305.7   632.6 2315.41   656.3 2328.08
  690.642343.147   737.6 2359.12   772.6 2372.68   807.7 2387.46     829 2395.24
#Mann= 6 ,-1 , 0
       0     .12       0   50.75      .1       0  315.36    .055       0
   399.9    .045       0   414.9      .1       0  690.64     .12       0
#XS Ineff= 2 , 0
                          457.23         2249.29
Permanent Ineff=
       F       F
Bank Sta=399.9,414.9
XS Rating Curve= 0 ,0
Exp/Cntr=0.3,0.1

Type RM Length L Ch R = 1 ,2129    ,224,223.8,223.1
XS GIS Cut Line= 2
2438807.86324788  556942.26173082438215.52580459557544.724600469
#Sta/Elev= 30
       0 2327.99    52.9  2311.1    84.7 2299.46  107.662292.185     151  2281.9
  193.15 2274.88  230.852269.681   306.5 2260.83  356.512256.856   363.1 2254.58
   376.4 2244.97   382.72242.833   388.5 2242.22   395.92242.887   411.2 2244.57
   426.8 2244.34   438.1 2246.09   475.1 2244.26     479 2244.93   482.9  2246.9
   494.2 2255.92     515 2268.23   561.5 2290.04   569.5 2294.62   583.9 2297.75
   595.1 2303.98  683.232340.891  723.63 2356.94   774.6 2374.84   844.9 2401.31
#Mann= 9 ,-1 , 0
       0      .1       0  107.66     .12       0  193.15      .1       0
  230.85    .055       0  356.51      .1       0   382.7    .045       0
   395.9      .1       0  683.23     .12       0  723.63      .1       0
#XS Ineff= 2 , 0
                          439.18         2246.14
Permanent Ineff=
       F       F
Bank Sta=382.7,395.9
XS Rating Curve= 0 ,0
Exp/Cntr(USF)=0,0
Exp/Cntr=0.3,0.1

Type RM Length L Ch R = 1 ,1905    ,131.6,131.4,131.2
XS GIS Cut Line= 3
2438729.87612679556870.0257029682438453.47332454557035.078139292
2438091.40755829557411.476702968
#Sta/Elev= 30
       0 2320.13    9.632317.544   22.992313.781    63.7 2303.53    78.1 2297.39
   107.7 2289.53   166.1 2282.25   213.2 2272.49   227.2 2267.58  236.682267.095
   288.6 2258.36   306.4 2257.28  347.032251.744   360.2  2248.2   371.9 2242.06
   423.9 2241.19   433.8 2237.33   437.9 2236.26   446.52237.512   464.2 2239.79
   498.9 2255.45   521.9 2269.56   556.5 2286.54   569.6 2289.06   592.2 2301.59
   654.3 2329.17     663 2331.07   683.5 2341.06  843.832399.278   844.2 2399.44
#Mann= 8 ,-1 , 0
       0     .12       0    9.63      .1       0   22.99     .12       0
  236.68    .055       0  347.03      .1       0   433.8    .045       0
   446.5      .1       0  843.83     .12       0
Bank Sta=433.8,446.5
XS Rating Curve= 0 ,0
Exp/Cntr=0.3,0.1

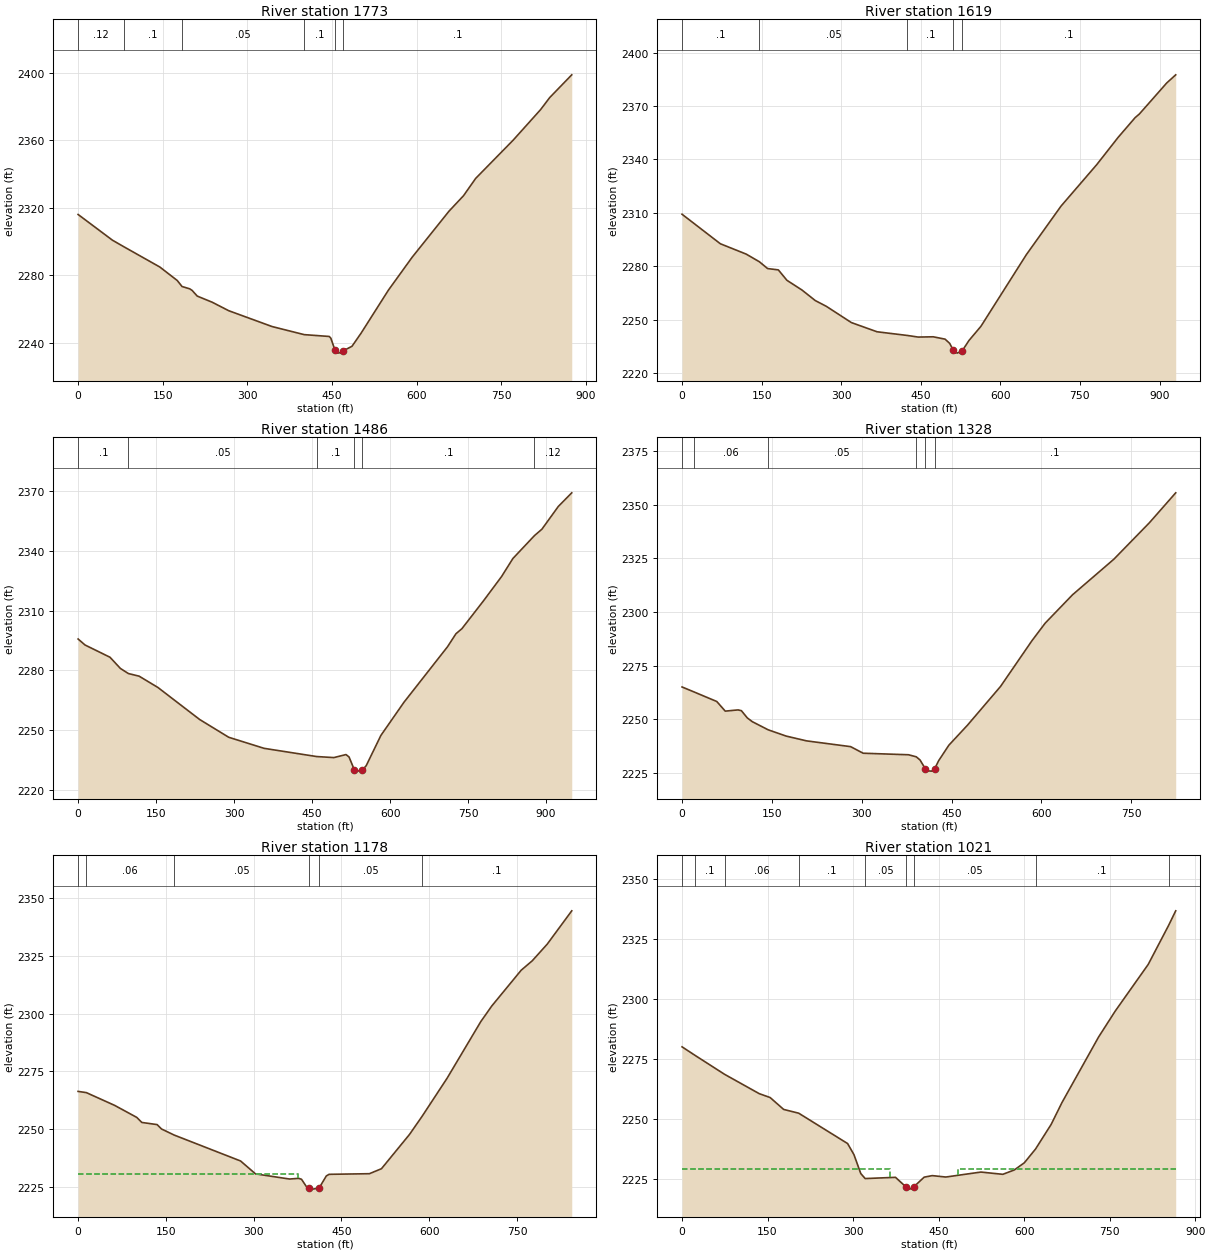
Type RM Length L Ch R = 1 ,1773    ,154.4,154.8,154.9
XS GIS Cut Line= 3
2438673.92539827556793.0612663652438362.46755318556939.479446825
     2437999.801      557327.081
#Sta/Elev= 30
       0 2316.12    60.9 2300.87    80.92297.024   144.9 2284.96   175.8 2276.96
  184.212273.412   197.9 2272.03   202.3 2271.03   211.2 2267.73   237.7 2264.09
     267 2259.06   343.8 2249.67  400.842244.869   445.2 2243.79     448 2242.76
   455.32235.732   458.1 2234.38   462.2 2233.91   470.42235.368   485.5 2237.97
   501.9  2245.9   549.9 2271.19   592.3 2290.85   657.4 2318.06   683.2 2327.26
   704.6 2337.47     771 2360.13   819.6 2378.22     836 2385.46     875 2398.92
#Mann= 6 ,-1 , 0
       0     .12       0    80.9      .1       0  184.21     .05       0
  400.84      .1       0   455.3    .045       0   470.4      .1       0
Bank Sta=455.3,470.4
XS Rating Curve= 0 ,0
Exp/Cntr=0.3,0.1

Type RM Length L Ch R = 1 ,1619    ,131.4,132.2,132.7
XS GIS Cut Line= 3
2438634.16396167556743.2698323182438289.77893138556797.130619339
     2437882.957      557213.296
#Sta/Elev= 30
       0 2309.23    72.2 2292.65   120.8 2286.85  145.822282.522   161.3 2278.71
   181.5 2277.97   197.7 2272.11   226.1 2266.64     251 2260.75     272 2257.48
   319.2 2248.35   367.5 2243.19  424.782241.112   445.1 2240.21   473.4 2240.37
   495.8 2239.04   504.5 2236.65   511.5 2232.68   518.5 2231.19   528.12232.492
   540.9 2238.32   563.3 2246.23   648.7  2286.4   714.3 2313.79   781.7 2337.13
     822 2352.44   854.1 2363.55     862 2365.56   913.5 2382.98   930.5 2387.58
#Mann= 5 ,-1 , 0
       0      .1       0  145.82     .05       0  424.78      .1       0
   511.5    .045       0   528.1      .1       0
Bank Sta=511.5,528.1
XS Rating Curve= 0 ,0
Exp/Cntr=0.3,0.1

Type RM Length L Ch R = 1 ,1486    ,158.8,158.4,157.6
XS GIS Cut Line= 3
  2438576.085954 556695.147106352438197.02040083556714.216449381
     2437780.053      557102.604
#Sta/Elev= 30
       0 2295.78    13.3 2292.77    61.4  2286.6    81.4 2280.97   96.782278.413
   117.4  2277.1   153.5 2271.42   233.8 2255.33   289.6 2246.41   357.7 2240.84
  458.512236.724   491.8 2236.19   515.2 2237.71   521.1 2236.49   531.4 2229.97
   537.1 2229.39   546.82229.947   554.1 2232.13   582.3 2247.31   626.7 2263.99
   710.5 2291.89   726.7 2298.42   738.2 2300.98   779.3 2314.83   814.5 2327.18
   836.2 2336.22  877.732347.733     892 2350.94   923.6 2362.39   949.4 2369.22
#Mann= 6 ,-1 , 0
       0      .1       0   96.78     .05       0  458.51      .1       0
   531.4    .045       0   546.8      .1       0  877.73     .12       0
Bank Sta=531.4,546.8
XS Rating Curve= 0 ,0
Exp/Cntr=0.3,0.1

Type RM Length L Ch R = 1 ,1328    ,146.8,150.5,153.2
XS GIS Cut Line= 2
      2438249.82      556423.755     2437674.768      557014.238
#Sta/Elev= 30
       0 2265.03   20.182262.689      58 2258.25    72.1 2253.76    93.5 2254.33
    99.1 2253.97   108.9 2250.61   117.3 2248.84  143.812245.048   173.9 2242.12
   207.9 2239.89   281.4  2237.2   302.4 2234.13   378.2 2233.41  391.062232.456
   397.4 2230.95   406.1 2226.91   411.3 2225.88     417 2225.78   421.72226.818
   428.4 2230.64   445.4 2237.85   476.6 2247.22   531.7 2265.26     584 2286.53
   606.2 2294.77   651.9 2308.01   720.9  2324.6   780.2 2341.59   824.2 2355.57
#Mann= 6 ,-1 , 0
       0      .1       0   20.18     .06       0  143.81     .05       0
  391.06      .1       0   406.1    .045       0   421.7      .1       0
Bank Sta=406.1,421.7
XS Rating Curve= 0 ,0
Exp/Cntr=0.3,0.1

Type RM Length L Ch R = 1 ,1178    ,161.8,156.4,150.8
XS GIS Cut Line= 4
2438122.85887832556304.5528757622437974.20314251556540.619817687
2437768.19344938556668.7764136032437653.81926637556969.830413603
#Sta/Elev= 30
       0 2266.33   14.042265.802    62.5 2260.26   100.2 2255.06   108.9 2252.86
     135 2251.93   142.6 2250.02  164.192247.392   277.7 2236.14   303.2 2230.55
   361.3 2228.32   377.1 2228.61   381.8 2228.21   390.4 2224.93     395 2224.33
   400.7 2223.94   411.8  2224.4   424.2 2229.66   428.9 2230.36   497.8 2230.63
   518.4 2232.79   566.4 2247.68  587.762255.484   630.6 2272.05   688.2 2296.62
     707  2303.4   757.2 2318.89   776.1 2322.98   801.8 2330.24   843.6 2344.65
#Mann= 6 ,-1 , 0
       0      .1       0   14.04     .06       0  164.19     .05       0
     395    .045       0   411.8     .05       0  587.76      .1       0
#XS Ineff= 2 , 0
          375.44 2230.35
Permanent Ineff=
       F       F
Bank Sta=395,411.8
XS Rating Curve= 0 ,0
Exp/Cntr=0.3,0.1

Type RM Length L Ch R = 1 ,1021    ,124,122.3,120.5
XS GIS Cut Line= 2
     2438001.363      556140.375     2437536.633      556870.948
#Sta/Elev= 30
       0 2280.16   22.492276.655   74.832268.694   135.5 2260.67   154.5 2259.07
   178.2 2254.12  204.63 2252.55   290.4 2239.92   301.5 2235.32   313.5 2227.44
  321.252225.354   374.4 2225.87     3922222.045   399.6 2220.96   406.92222.012
   424.7 2225.94   438.9 2226.58   462.6 2225.99   524.2 2228.06   562.7 2227.12
     583 2228.96   600.4 2231.93  620.012237.635   647.5 2247.92   666.4 2256.98
   730.7 2284.27   759.7    2295   817.7 2314.46  853.622330.767   865.9 2336.75
#Mann= 9 ,-1 , 0
       0      .1       0   22.49      .1       0   74.83     .06       0
  204.63      .1       0  321.25     .05       0     392    .045       0
   406.9     .05       0  620.01      .1       0  853.62     .12       0
#XS Ineff= 2 , 0
          365.11 2229.33  484.03         2229.26
Permanent Ineff=
       F       F
Bank Sta=392,406.9
XS Rating Curve= 0 ,0
Exp/Cntr=0.3,0.1

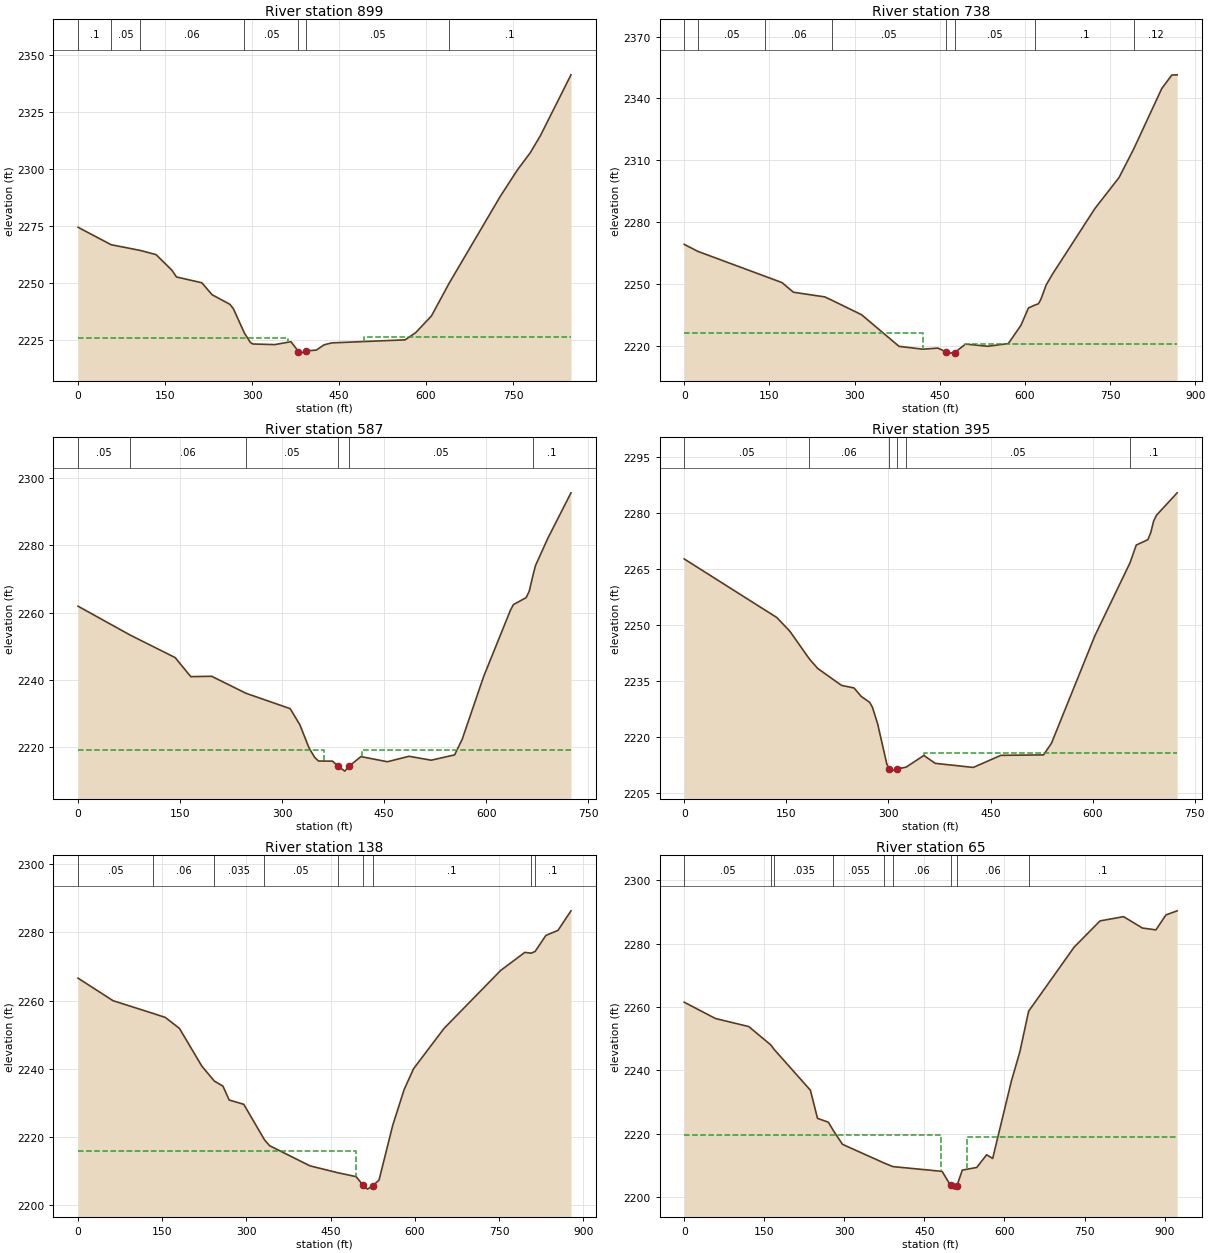
Type RM Length L Ch R = 1 ,899     ,159.8,161,161.8
XS GIS Cut Line= 2
2437834.42526892556076.1637055242437484.68643149556850.723857873
#Sta/Elev= 30
       0 2274.38   57.052266.713  107.012264.221   134.5 2262.36   161.9  2255.5
   169.6 2252.55   213.5 2249.98     231 2244.75   261.8 2240.51   267.7 2238.64
   286.92227.858   296.9 2223.82   301.3 2223.08   339.1 2222.81   367.1 2224.08
     3802219.772   384.6 2219.06   393.4    2220     411 2220.42   424.1  2222.7
   437.3 2223.56     564  2224.9   582.1 2228.06   609.3  2235.4  639.35 2249.57
   727.8 2287.88   757.4 2299.54   779.6 2307.12   797.1 2314.62   849.9  2341.4
#Mann= 7 ,-1 , 0
       0      .1       0   57.05     .05       0  107.01     .06       0
   286.9     .05       0     380    .045       0   393.4     .05       0
  639.35      .1       0
#XS Ineff= 2 , 0
          362.21 2225.63  493.56         2226.11
Permanent Ineff=
       F       F
Bank Sta=380,393.4
XS Rating Curve= 0 ,0
Exp/Cntr=0.3,0.1

Type RM Length L Ch R = 1 ,738     ,142.4,151.1,158.9
XS GIS Cut Line= 2
       2437719.9      556023.348      2437346.25      556807.132
#Sta/Elev= 30
       0 2269.36   24.24 2265.93  142.32  2253.9   172.2 2250.84   192.4 2246.17
   247.5 2243.91   260.42242.261   312.4 2235.28   378.4 2219.96   420.3 2218.59
   446.9 2219.12   460.82217.324   468.4 2216.68   476.4 2216.95   495.6 2221.08
   534.4 2219.99   570.9  2221.3   593.1 2230.15   606.4 2238.56  617.91 2239.98
   624.1 2240.61   628.5  2242.9   637.4 2249.61   648.6  2254.9   723.4  2286.7
   765.9 2301.69  792.382315.898   841.2 2344.83   858.9 2351.35   868.3 2351.46
#Mann= 8 ,-1 , 0
       0      .1       0   24.24     .05       0  142.32     .06       0
   260.4     .05       0   460.8    .045       0   476.4     .05       0
  617.91      .1       0  792.38     .12       0
#XS Ineff= 2 , 0
          419.89 2226.23  494.57         2221.22
Permanent Ineff=
       F       F
Bank Sta=460.8,476.4
XS Rating Curve= 0 ,0
Exp/Cntr=0.3,0.1

Type RM Length L Ch R = 1 ,587     ,201.8,191.8,185.1
XS GIS Cut Line= 4
2437609.68779279556019.1603590652437457.80639708556322.923150495
2437363.30241752556371.8627113372437221.54644819556611.497802354
#Sta/Elev= 30
       0 2261.88   76.972253.256   142.7  2246.6   165.7 2240.93   196.3 2241.05
  246.862235.987   311.8 2231.41     326 2226.64   339.6 2219.68   347.9 2216.89
   353.5 2215.84     374 2215.81   382.7 2214.23   392.1 2212.84     398 2214.25
   415.8 2217.16   454.6 2215.63   486.5 2217.25   519.1 2216.09   553.5 2217.67
   564.6 2222.31     596 2240.89   635.3 2260.58   639.9 2262.36   658.5 2264.41
   663.1 2266.29  668.752271.146   672.4    2274   690.7 2282.16   724.5 2295.59
#Mann= 6 ,-1 , 0
       0     .05       0   76.97     .06       0  246.86     .05       0
   382.7    .045       0     398     .05       0  668.75      .1       0
#XS Ineff= 2 , 0
          362.16 2219.12  416.88         2219.03
Permanent Ineff=
       F       F
Bank Sta=382.7,398
XS Rating Curve= 0 ,0
Exp/Cntr(USF)=0,0
Exp/Cntr=0.3,0.1

Type RM Length L Ch R = 1 ,395     ,257.1,257.4,257.7
XS GIS Cut Line= 4
2437483.47182675555934.1004112782437331.38208893556136.192254683
2437248.33692524556402.8493169262437182.81333271 556583.14857598
#Sta/Elev= 30
       0 2267.67     136 2251.98   155.1 2248.32  183.882240.866   196.1 2238.33
   231.1 2233.79   249.4 2233.11   259.8 2230.87   272.4 2229.25   276.6 2227.87
   284.1  2223.5   297.5 2212.81   300.62211.389   303.2 2210.82   312.4 2211.37
  326.082211.902     352 2215.02   368.7 2212.91   424.6 2211.81   465.1 2215.05
   527.9 2215.17   539.5 2218.31   603.2 2247.08   654.9 2266.66     664 2271.39
     681 2272.83   685.3  2274.7   689.5 2277.81   693.8  2279.4   724.1 2285.39
#Mann= 6 ,-1 , 0
       0     .05       0  183.88     .06       0   300.6    .045       0
   312.4     .06       0  326.08     .05       0   654.9      .1       0
#XS Ineff= 2 , 0
                          351.96         2215.74
Permanent Ineff=
       F       F
Bank Sta=300.6,312.4
XS Rating Curve= 0 ,0
Exp/Cntr(USF)=0,0
Exp/Cntr=0.3,0.1

Type RM Length L Ch R = 1 ,138     ,68.5,72.6,76.5
XS GIS Cut Line= 4
2437470.97130035555936.183832344  2437081.371561556204.945149863
2437060.53735034556317.4498874292437168.85441157556586.940402321
#Sta/Elev= 30
       0  2266.6    62.3    2260  132.822256.312   155.6 2255.08   180.7 2251.86
   220.4 2240.85  242.752236.449   258.1 2234.96   269.3 2230.88   295.2 2229.63
  332.052219.241   341.2  2217.5   413.1 2211.59  462.622209.573   495.5 2208.42
   507.92205.857   515.8 2204.76     525 2205.75   536.2 2207.39   560.6 2223.45
   580.9 2233.92   597.7 2240.05   652.1 2251.88   752.9 2268.86     796 2274.16
  807.332273.924  814.312274.434   833.5 2279.13     855  2280.6   878.2 2286.34
#Mann= 9 ,-1 , 0
       0     .05       0  132.82     .06       0  242.75    .035       0
  332.05     .05       0  462.62     .06       0   507.9    .045       0
     525      .1       0  807.33     .05       0  814.31      .1       0
#XS Ineff= 2 , 0
          494.73  2215.8
Permanent Ineff=
       F       F
Bank Sta=507.9,525
XS Rating Curve= 0 ,0
Exp/Cntr(USF)=0,0
Exp/Cntr=0.5,0.3

Type RM Length L Ch R = 1 ,65      ,60.8,61.6,66.7
XS GIS Cut Line= 4
2437398.05156304555919.5164638152437027.20261329  556190.3612024
2436966.78340237556292.4488346362437112.81038489556605.712026126
#Sta/Elev= 30
       0 2261.53    58.4 2256.39   120.8 2253.85  162.352248.031  168.242246.673
   236.4 2233.75   249.7 2224.88     270 2223.66  279.642220.947   296.5 2216.68
  374.912210.748  391.042209.649   483.2 2208.14     499  2203.7   506.2 2202.54
   510.8 2203.59     521 2208.55     548 2209.38   566.6  2213.4   577.9 2212.22
   612.8 2236.55   628.9 2245.95  645.282258.698   730.4 2278.89     779 2287.19
   823.1 2288.53   858.4 2284.94   883.7 2284.36   902.5 2289.08   923.5 2290.37
#Mann= 9 ,-1 , 0
       0     .05       0  162.35     .06       0  168.24    .035       0
  279.64    .055       0  374.91     .05       0  391.04     .06       0
     499    .045       0   510.8     .06       0  645.28      .1       0
#XS Ineff= 2 , 0
          480.41 2219.63   529.3         2218.88
Permanent Ineff=
       F       F
Bank Sta=499,510.8
XS Rating Curve= 0 ,0
Exp/Cntr(USF)=0,0
Exp/Cntr=0.5,0.3

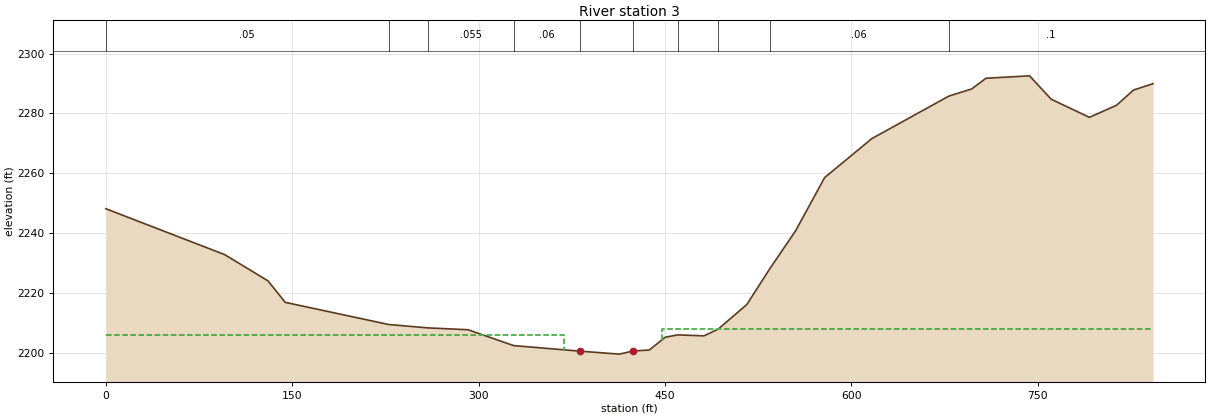
Type RM Length L Ch R = 1 ,3       ,,,
XS GIS Cut Line= 4
2437252.76692655555951.6175066662436991.71212002556135.996717835
2436928.26764631556235.1822889772437092.63815738556605.749645579
#Sta/Elev= 30
       0 2248.19    95.6 2232.87   130.5  2224.1   144.4 2216.92   227.5 2209.53
   259.2 2208.39   291.4 2207.78   328.2 2202.48   381.72200.616   413.3 2199.63
   424.52200.695   437.3 2200.99   450.2 2205.27   460.2 2206.05   481.4 2205.73
   492.8 2207.99   515.8 2216.18   534.1 2228.01   555.2 2240.89   578.4 2258.56
   616.4 2271.59   678.5 2285.81   696.7 2288.16   708.3 2291.75   743.3 2292.56
   760.8 2284.73   791.5  2278.7   813.3 2282.73     827 2287.81   842.7 2289.94
#Mann= 10 ,-1 , 0
       0     .05       0   227.5     .06       0   259.2    .055       0
   328.2     .06       0   381.7    .045       0   424.5      .1       0
   460.2     .06       0   492.8    .045       0   534.1     .06       0
   678.5      .1       0
#XS Ineff= 2 , 0
          368.79 2206.15  447.25         2208.11
Permanent Ineff=
       F       F
Bank Sta=381.7,424.5
XS Rating Curve= 0 ,0
Exp/Cntr(USF)=0,0
Exp/Cntr=0.5,0.3
LCMann Table=0

Chan Stop Cuts=-1
Use User Specified Reach Order=0
Composite Channel Slope=5